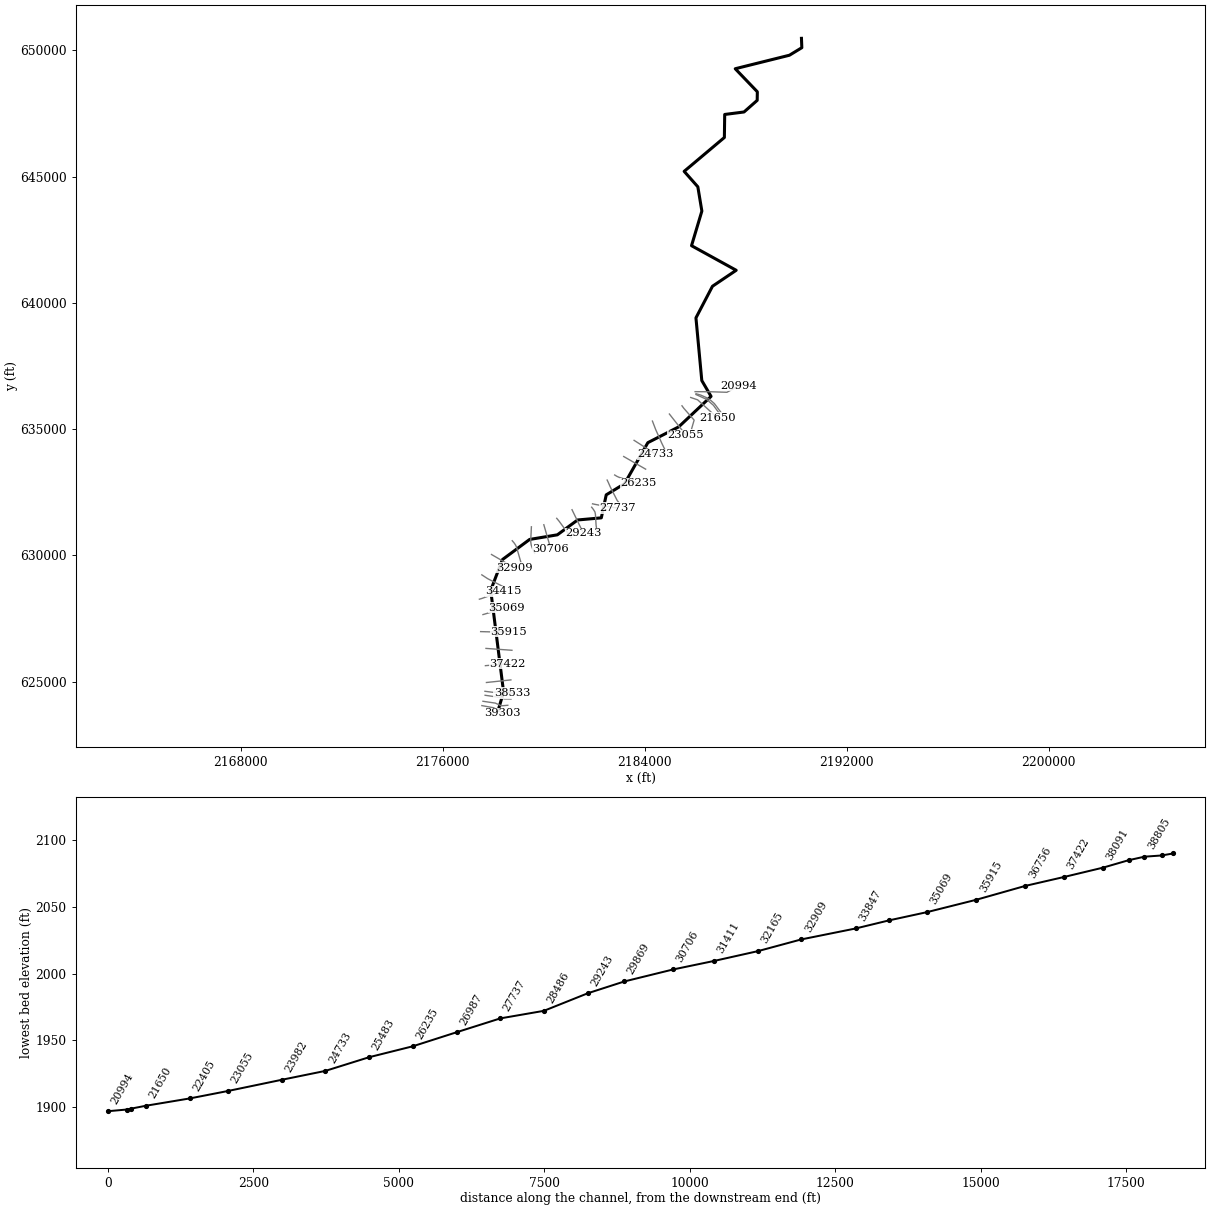
--- RFBUCKRV.prj (project) ---

Proj Title=RFBUCKRV
Current Plan=p01
Default Exp/Contr=0,0
English Units
Geom File=g01
Flow File=f01
Plan File=p01
BEGIN DESCRIPTION:
---------- MODELED AS PART OF WVEMD CTP PROGRAM, 2023----------
Stream Name: Right Fork Buckhannon River
Flood Zone:  AFH
Upshur County, WV
HEC-RAS Version: RAS 6.3
Vertical Datum: NAVD88
Projection: NAD 1983 StatePlane West Virginia S FIPS 4702 (US Feet)
Terrain: 1-meter LIDAR (FEMA Region III 3DEP collected 2016-2018)
Land Use: 2019 NLCD
Hydrologic Method:
Gage-Weighted WV 2010 RRE
Additional Model Notes:
KWSE tie-in to BUCKHANR_U; four shared XS at US extent with RFBUCKHRV in Randolph County
KWSE applied to XSs 38805 and 38533 to acheive tie-in to Randolph model
END DESCRIPTION:
DSS Export Rating Curves= 0
DSS Export Rating Curve Sorted= 0
DSS Export Volume Flow Curves= 0
DXF OffsetX= 0
DXF OffsetY= 0
DXF ScaleX= 0
DXF ScaleY= 0

--- RFBUCKRV.p01 (plan) ---

Plan Title=Floodplain
Program Version=6.31
Short Identifier=Floodplain
Geom File=g01
Flow File=f01
Subcritical Flow
K Sum by GR= 0
Std Step Tol= 0.01
Critical Tol= 0.01
Num of Std Step Trials= 20
Max Error Tol= 0.3
Flow Tol Ratio= 0.001
Split Flow NTrial= 30
Split Flow Tol= 0.02
Split Flow Ratio= 0.02
Log Output Level= 0
Friction Slope Method= 1
Unsteady Friction Slope Method= 2
Unsteady Bridges Friction Slope Method= 1
Parabolic Critical Depth
Global Vel Dist= 0 , 0 , 0
Global Log Level= 0
CheckData=True
Encroach Param=-1 ,0,0, 0
Mapping Interval=1HOUR
Computation Time Step Use Courant=        0
Computation Time Step Use Time Series=    0
Computation Time Step Count To Double=0
Computation Time Step Max Doubling=0
Computation Time Step Max Halving=0
Computation Time Step Residence Courant=0
Run HTab= 0
Run UNet= 0
Run Sediment= 0
Run PostProcess= 0
Run WQNet= 0
Run RASMapper=-1
UNET Theta= 0
UNET Theta Warmup= 0
UNET ZTol= 0
UNET ZSATol= 0
UNET MxIter= 0
UNET Max Iter WO Improvement= 0
UNET MaxInSteps= 0
UNET DtIC= 0
UNET DtMin= 0
UNET MaxCRTS= 0
UNET WFStab= 0
UNET SFStab= 0
UNET WFX= 1
UNET SFX= 1
UNET Gravity=32.17405
UNET 1D Methodology=Finite Difference
UNET DSS MLevel= 1
UNET Pardiso=0
UNET DZMax Abort= 0
UNET Use Existing IB Tables= 0
UNET Froude Reduction=False
UNET Froude Limit= 0
UNET Froude Power= 0
UNET D1 Cores= 0
UNET WindReference=Eulerian
UNET WindDragFormulation=Hsu (1988)
UNET D2 Coriolis=0
UNET D2 Cores= 0
UNET D2 Theta= 1
UNET D2 Theta Warmup= 1
UNET D2 Z Tol= 0.01
UNET D2 Volume Tol= 0.01
UNET D2 Max Iterations= 20
UNET D2 Equation= 0
UNET D2 RampUpFraction=0.1
UNET D2 TimeSlices= 1
UNET D2 Turbulence Formulation=Non-Conservative (original)
UNET D2 Eddy Viscosity=0.3
UNET D2 Transverse Eddy Viscosity=0.1
UNET D2 Smagorinsky Mixing=0
UNET D2 BCVolumeCheck=0
UNET D2 Cores=0
UNET D2 SolverType=PARDISO (Direct)
UNET D2 Minimum Iterations= 3
UNET D2 Maximum Iterations= 30
UNET D2 Restart Number= 10
UNET D2 Relaxation Coeff=1.3
UNET D2 SOR Precondition Iterations= 10
UNET D2 ILUT Maximum Fill= 8
UNET D2 ILUT Tolerance=1E-08
UNET D2 Convergence Tolerance=0.00001
UNET D1D2 MaxIter= 0
UNET D1D2 ZTol=0.01
UNET D1D2 QTol=0.1
UNET D1D2 MinQTol=1
Write IC File= 0
Write IC File at Fixed DateTime=0
Write IC File at Sim End=0
Echo Input=False
Echo Parameters=False
Echo Output=False
Write Detailed= 0
HDF Write Warmup=0
HDF Write Time Slices=0
HDF Flush=0
HDF Compression= 1
HDF Chunk Size= 1
HDF Spatial Parts= 1
HDF Use Max Rows=0
HDF Fixed Rows= 1
Calibration Method= 0
Calibration Iterations= 20
Calibration Max Change=0.05
Calibration Tolerance=0.2
Calibration Maximum=1.5
Calibration Minimum=0.5
Calibration Optimization Method= 1
WQ AD Non Conservative
WQ ULTIMATE=-1
WQ Max Comp Step=1HOUR
WQ Output Interval=15MIN
WQ Output Selected Increments= 0
WQ Create Restart=0
WQ Fixed Restart=0
WQ System Summary=0
WQ Write To DSS=0
Sorting and Armoring Iterations= 10
XS Update Threshold= 0.02
Bed Roughness Predictor= 0
Hydraulics Update Threshold= 0.02
Energy Slope Method= 1
Volume Change Method= 1
Sediment Retention Method= 0
Sediment TS Multiplier= 1
Warm Up Method= 0
XS Weighting Method= 0
Number of US Weighted Cross Sections= 1
Number of DS Weighted Cross Sections= 1
Upstream XS Weight=0
Main XS Weight=1
Downstream XS Weight=0
Number of DS XS's Weighted with US Boundary= 1
Upstream Boundary Weight= 1
Weight of XSs Associated with US Boundary= 0
Number of US XS's Weighted with DS Boundary= 1
Downstream Boundary Weight= 0.5
Weight of XSs Associated with DS Boundary= 0.5
Percentile Method= 0
Sediment Output Level= 3
Mass or Volume Output= 0
Output Increment Type= 1
Profile and TS Output Increment= 1
Transport Output Increment 1
XS Output Flag= 0
XS Output Increment= 10
Read HDF5 Sediment Hotstart= 0
Sediment Hotstart Type= 0
Write Gradation File= 0
Read Gradation Hotstart= 0
Write HDF5 File= 1
Write Binary Output= 1
Write DSS Sediment File= 0
DSS Sediment Output Type= 1
SV Curve= 0
Specific Gage Flag= 0
Subcell Erosion Methods= 0
Subcell Deposition Methods= 0
Advection Scheme= 1
Matrix Solver= 0
Implicit Weighting Factor= 1
Maximum Outer Loop Convergence Iterations= 5
Convergence Maximum Absolute= 0.001
Convergence RMSE= 0.0001
Grain Fractions Max Abs Error= 0.001
Max Subgrid Regions= 1
Max Subgrid Length Scale= 3.402823E+38
Initial Layer Thickness= 3.402823E+38
Min Layer Thickness= 3.402823E+38
Max Layer Thickness= 3.402823E+38
Number of Layers= 5

--- RFBUCKRV.f01 (steady flow) ---

Flow Title=Flows
Program Version=6.31
Number of Profiles= 1
Profile Names=01pct
River Rch & RM=RFBUCKRV,Main            ,39303
    2620
River Rch & RM=RFBUCKRV,Main            ,38091
    3050
River Rch & RM=RFBUCKRV,Main            ,22405
    3950
River Rch & RM=RFBUCKRV,Main            ,20994
    6310
River Rch & RM=RFBUCKRV,Main            ,17638
    7070
River Rch & RM=RFBUCKRV,Main            ,0
   12700
Boundary for River Rch & Prof#=RFBUCKRV,Main            , 1
Up Type= 0
Dn Type= 1
Dn Known WS=1847.9
Set Internal Change=RFBUCKRV        ,Main            ,38805   , 1 , 3 ,2093.3
Set Internal Change=RFBUCKRV        ,Main            ,38533   , 1 , 3 ,2090.5
DSS Import GetInterval= 0
DSS Import GetPeak= 0
DSS Import FillOption= 0

--- RFBUCKRV.g01 (geometry) ---

Geom Title=Geometry
Program Version=6.31

River Reach=RFBUCKRV        ,Main
Reach XY= 30
2178199.31550507623875.187013677      2178410.41624590.075000018
2177901.58900002628619.7920000112178366.86300004629835.502000019
2179442.34572136630632.0493522732180541.76500003630815.556000009
2181342.78670636631403.2214415672182281.78499998631487.640000016
2182476.89100003632398.700000003     2183201.287632838.447999999
2184125.48100001634465.8620000182185347.69005939 635091.10039711
2186629.04300004636298.5699999932186262.12400004636925.754999995
2186030.44947812639409.0417435322186685.01939791640660.844598621
2187624.86500001641293.6749999972185855.19900002642267.863000005
2186264.92800003643637.815000013      2186105.22644599.812000006
2185563.54099999645211.9449999932187156.41500002646553.281000018
2187169.43500003647465.5999999942187934.38000003647563.696999997
2188456.08500002648023.763000011     2188462.152648364.040999994
2187586.29000002649276.7029999942189732.80500004 649811.42900002
2190224.12000005650110.0409999942190209.65502311650480.805280581

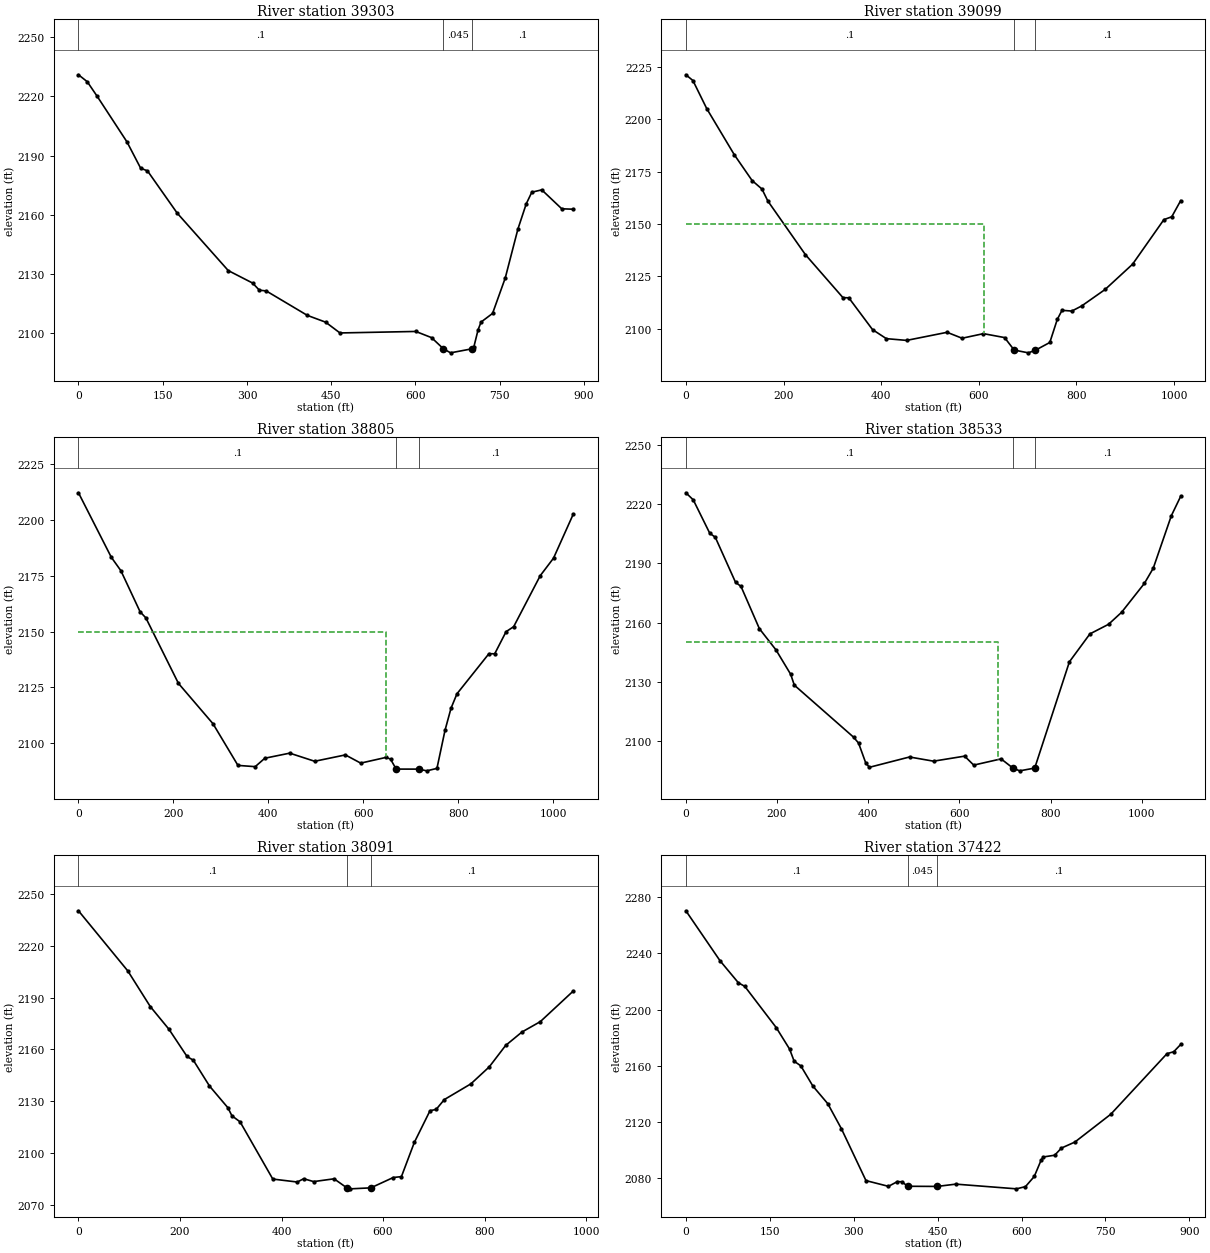
Type RM Length L Ch R = 1 ,39303   ,203.4,203.9,205.4
XS GIS Cut Line= 4
2177551.24040204624050.3350712962178005.07846729623967.837323061
2178233.57108395623858.8600359972178353.18372564 623742.90207239
#Sta/Elev= 30
       0 2230.89    15.6  2227.4    33.5 2219.91    86.3 2196.93   110.7 2183.59
   122.9 2182.22   175.8 2160.83   266.7 2131.74   309.9 2125.44   322.1 2121.81
   334.3 2121.43   407.5 2109.05     440 2105.62   465.6 2100.15   600.6 2100.91
   628.7 2097.78  649.68 2092.15   662.6 2090.08  701.11 2092.15     704 2093.09
   711.6 2101.82   716.8 2105.66   737.3 2110.04   759.9 2127.99   782.5 2152.83
   797.3 2165.56   807.2 2171.43   824.9 2172.61   860.5 2163.03     881 2162.81
#Mann= 3 ,-1,0
       0      .1       0  649.68    .045       0  701.11      .1       0
Bank Sta=649.68,701.11
XS Rating Curve= 0 ,0
Exp/Cntr=0.3,0.1

Type RM Length L Ch R = 1 ,39099   ,291.6,293.6,294.8
XS GIS Cut Line= 4
2177593.93590173624222.3079664692178083.07584922624149.911434709
2178322.93905187624042.5527706432178578.40188867 624063.60543718
#Sta/Elev= 30
       0 2221.23    14.4 2218.49    42.7  2205.1    99.3 2183.03   135.7 2170.75
   155.9 2166.69     168 2160.95   244.9 2135.38   321.7 2114.89   333.8 2114.78
   382.4 2099.61   410.7  2095.3   452.2 2094.47   535.1 2098.33   565.8  2095.5
   609.6 2097.69   652.9 2095.81   672.5 2089.86   701.5 2088.53  715.97 2089.77
   745.5 2093.47   760.8 2104.47   770.5 2108.82   790.6 2108.47   810.7 2110.89
   858.8 2118.77     915 2130.81   979.2  2152.1   995.3 2153.46  1013.6 2161.16
#Mann= 3 ,-1,0
       0      .1       0   672.5    .045       0  715.97      .1       0
#XS Ineff= 2 , 0
             610    2150
Permanent Ineff=
       F       F
Bank Sta=672.5,715.97
XS Rating Curve= 0 ,0
Exp/Cntr=0.3,0.1

Type RM Length L Ch R = 1 ,38805   ,258.2,272.8,283.5
XS GIS Cut Line= 4
2177679.68873024624460.1819114652178298.44191138624368.948076121
 2178444.8745414624313.894040776 2178705.7497801624311.258883478
#Sta/Elev= 30
       0 2212.27    69.2 2183.36    89.4 2177.34   129.9 2158.92     142  2156.2
   210.7 2126.82   283.5 2108.74   336.1 2090.06   372.5 2089.49   392.7 2093.27
   445.2 2095.55   497.8 2091.91   562.5 2094.76   594.8 2091.08   648.7 2093.67
   657.7 2092.85  669.552088.406     717 2088.39   734.1 2087.62   755.5 2088.72
   772.6 2105.88   785.2 2115.71   797.7 2122.16   865.1 2140.15   877.2 2140.08
   901.2 2150.01   917.2 2152.25   973.2 2175.11  1001.2 2182.97  1042.8  2202.7
#Mann= 3 ,-1,0
       0      .1       0  669.55    .045       0     717      .1       0
#XS Ineff= 2 , 0
          648.66    2150
Permanent Ineff=
       F       F
Bank Sta=669.55,717
XS Rating Curve= 0 ,0
Exp/Cntr=0.3,0.1

Type RM Length L Ch R = 1 ,38533   ,437.6,441.7,439.1
XS GIS Cut Line= 4
2177672.14734679624617.7990620572177995.08973106624576.862703487
2178440.84119105624611.7344163432178747.10579961624548.055636345
#Sta/Elev= 30
       0  2225.7    16.2 2222.11    52.4 2205.22    64.5  2203.2   108.9 2180.41
     121 2178.28   161.3 2156.91   197.6 2146.21   229.9 2133.85   237.9 2128.35
   367.8 2102.03   378.8 2099.05   394.8 2088.85   402.8 2086.78   490.6 2091.99
   543.3 2089.87   611.5 2092.42   631.5 2087.88   691.5 2091.03  717.632086.354
   732.4 2084.98  765.282086.377   841.4 2140.16   886.4 2154.28   927.2 2159.13
   955.8 2165.19  1005.8 2179.81  1025.3  2187.5  1065.1 2214.14  1085.5 2223.89
#Mann= 3 ,-1,0
       0      .1       0  717.63    .045       0  765.28      .1       0
#XS Ineff= 2 , 0
             685    2150
Permanent Ineff=
       F       F
Bank Sta=717.63,765.28
XS Rating Curve= 0 ,0
Exp/Cntr=0.3,0.1

Type RM Length L Ch R = 1 ,38091   ,669.5,668.7,666.5
XS GIS Cut Line= 2
2177731.53552444624965.6252272192178700.70524872625069.023907995
#Sta/Elev= 30
       0 2240.18    97.2  2205.4   141.4 2184.82   178.3 2171.65   213.8 2155.95
   226.4  2153.7   258.1 2138.84   294.3  2126.3   302.3 2121.62   318.4 2118.11
   382.8 2085.03   431.1 2083.32   443.6 2085.23   463.3 2083.57   503.5 2085.18
   529.42079.815   535.7 2079.38   575.9 2079.95   620.1 2085.93   636.2 2086.45
   661.7 2106.29   692.5 2124.56   704.6 2125.32   720.7    2131     773 2140.09
   809.2 2149.91   841.4 2162.28   873.6 2170.06   909.8 2176.08   974.7 2193.77
#Mann= 3 ,-1,0
       0      .1       0   529.4    .045       0   575.9      .1       0
Bank Sta=529.4,575.9
XS Rating Curve= 0 ,0
Exp/Cntr(USF)=0,0
Exp/Cntr=0.3,0.1

Type RM Length L Ch R = 1 ,37422   ,657.9,666,645.5
XS GIS Cut Line= 2
2177691.41066324625632.3152286352178572.61434567625707.935159351
#Sta/Elev= 30
       0 2270.34      61 2234.79    93.9 2219.06   105.3 2216.53   161.4 2187.24
   185.4 2171.87   193.5 2163.26   205.5 2159.91     227 2145.55   253.7 2132.98
   277.8 2115.33   321.9 2078.25   362.1 2074.17   378.1 2077.56   386.2  2077.4
   396.42074.216   449.22074.108   482.5 2075.74   590.9 2072.39     607 2073.98
   622.7 2081.18   635.1 2092.96   639.1  2095.1   659.2 2096.32   671.2  2101.4
   695.3 2105.69   759.5 2125.51   859.9  2168.6     872    2170   884.4 2175.16
#Mann= 3 ,-1,0
       0      .1       0   396.4    .045       0   449.2      .1       0
Bank Sta=396.4,449.2
XS Rating Curve= 0 ,0
Exp/Cntr(USF)=0,0
Exp/Cntr=0.3,0.1

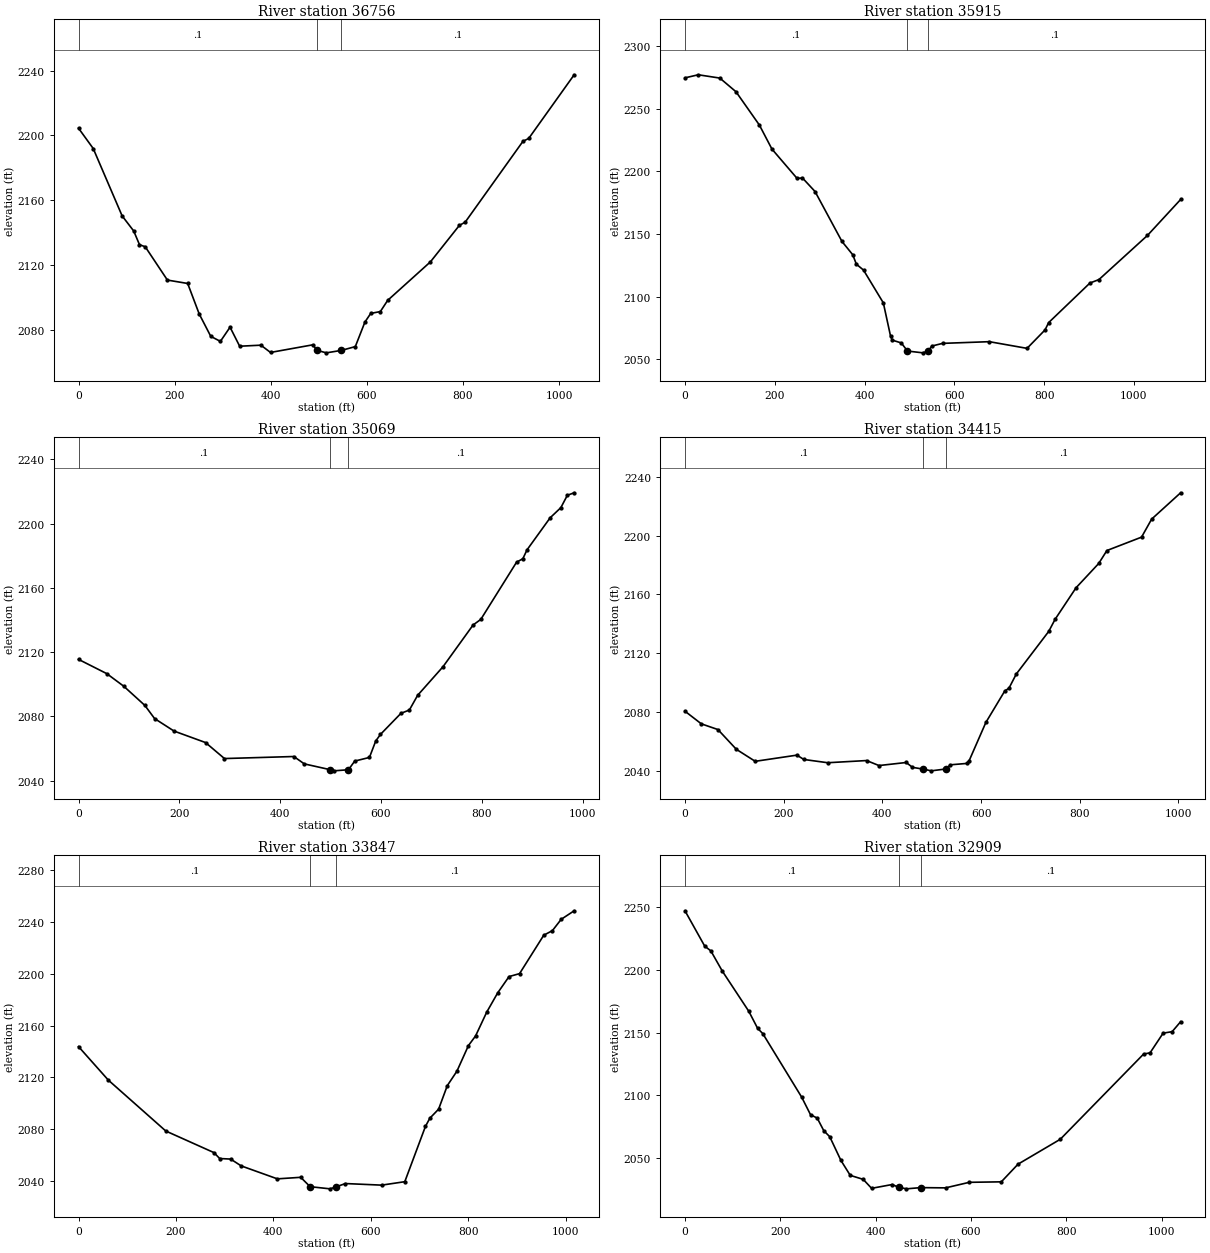
Type RM Length L Ch R = 1 ,36756   ,824.3,841,830.4
XS GIS Cut Line= 3
2177713.61070096626316.6159742942178656.18897355626248.078168832
2178742.47103334626241.739305839
#Sta/Elev= 30
       0 2204.44    30.6 2191.89    90.8 2150.27   114.9 2140.95   126.9  2132.5
   138.9 2131.21     185 2110.64   227.2 2108.54   251.2 2089.71   275.3 2075.87
   295.3 2072.78   315.4 2081.55   335.4 2069.79   379.6 2070.43   399.6 2065.94
   487.8 2070.66   496.4 2067.23   515.9  2065.7  547.172067.214   576.1 2069.55
   596.1 2084.71   608.2 2090.05   628.2 2091.19   643.5 2098.12   732.5 2121.91
   792.7 2144.42   804.7 2146.38     925 2196.33     937 2198.11  1031.6 2237.43
#Mann= 3 ,-1,0
       0      .1       0   496.4    .045       0  547.17      .1       0
Bank Sta=496.4,547.17
XS Rating Curve= 0 ,0
Exp/Cntr(USF)=0,0
Exp/Cntr=0.3,0.1

Type RM Length L Ch R = 1 ,35915   ,839.6,846.3,853.5
XS GIS Cut Line= 6
2177502.57928893 626981.467227252177600.98001076626978.773991168
2177791.53343542626973.5541853462178053.93514159626966.367848009
2178128.90677643626964.313718259 2178605.9745573626983.244103835
#Sta/Elev= 30
       0 2274.59    29.6 2277.04    77.6 2274.41   113.6 2263.52   165.7 2236.97
   193.7 2217.79   249.7 2194.41   261.7 2194.75   289.7 2183.95   349.7 2144.12
   373.7 2133.52   381.7 2126.02   397.7 2121.28   441.8 2095.16   457.8 2068.78
   461.8 2065.44   481.8 2063.21  495.622056.747   529.8 2055.31   541.8 2056.78
   549.8 2060.72   573.8 2062.86   677.9 2064.21   761.9 2058.88     802 2073.59
     810 2079.41     902 2110.98   922.1 2113.74  1030.1 2148.93    1104  2177.6
#Mann= 3 ,-1,0
       0      .1       0  495.62    .045       0   541.8      .1       0
Bank Sta=495.62,541.8
XS Rating Curve= 0 ,0
Exp/Cntr(USF)=0,0
Exp/Cntr=0.3,0.1

Type RM Length L Ch R = 1 ,35069   ,652.1,654.2,655.8
XS GIS Cut Line= 2
2177594.35652171627655.7280652542178537.91532255627932.260642015
#Sta/Elev= 30
       0 2115.45    56.1 2106.56    89.7 2098.73   131.6 2086.78   150.9 2078.59
   189.5  2070.8     252 2063.65   289.5 2053.69   427.1 2054.96   447.9 2050.37
   497.9 2046.85   506.3 2046.04   535.4 2046.71   547.9 2052.11   577.1 2054.39
   589.6 2064.63     599 2068.74   639.6 2081.85   656.3 2083.91   672.7 2093.06
     723 2110.86   782.7 2136.85     798 2140.34   868.9 2175.94   881.4 2178.13
   889.7 2183.65   935.6 2203.62   956.8 2209.93   969.7 2217.63   983.2 2219.18
#Mann= 3 ,-1,0
       0      .1       0   497.9    .045       0   535.4      .1       0
Bank Sta=497.9,535.4
XS Rating Curve= 0 ,0
Exp/Cntr(USF)=0,0
Exp/Cntr=0.3,0.1

Type RM Length L Ch R = 1 ,34415   ,585.1,567.9,535.1
XS GIS Cut Line= 6
2177452.46816868628265.8672175112177546.99652292628293.882581428
2177726.44301443628358.2003661692178214.77373068628533.228231341
2178308.58456667628558.6140073392178405.62669542628579.615277678
#Sta/Elev= 30
       0 2080.42    33.1 2071.83    66.8 2067.93   104.1 2054.49   142.3 2046.32
   226.9 2050.53   240.8 2047.58   289.2 2045.36     368 2046.84   393.1 2043.44
   448.3 2045.52     461 2042.21   482.3 2041.04   499.1 2039.84  529.532041.145
   537.5 2043.93   570.7 2044.87   575.8 2046.72   609.7 2072.76     648 2094.18
   656.5 2096.07   671.4 2105.75   737.1 2134.73     750 2142.96   792.5 2164.45
   838.4 2180.96     855 2189.78   925.2 2198.89   945.7 2211.17  1004.4 2229.08
#Mann= 3 ,-1,0
       0      .1       0   482.3    .045       0  529.53      .1       0
Bank Sta=482.3,529.53
XS Rating Curve= 0 ,0
Exp/Cntr(USF)=0,0
Exp/Cntr=0.3,0.1

Type RM Length L Ch R = 1 ,33847   ,938.3,937.5,935.9
XS GIS Cut Line= 3
2177548.92839991   629229.9299392177781.60084763629077.870516662
2178439.99145609628740.942054749
#Sta/Elev= 30
       0 2143.79    61.2 2117.88   179.2 2078.52     278 2061.83   289.8 2057.26
   312.3 2056.83   333.9 2051.57   408.2 2041.54   456.1 2042.73   475.5 2035.48
   516.5 2033.82     528 2035.26   547.9 2037.91   622.2 2036.68   669.8 2039.34
   712.2 2082.09   721.2 2088.41   739.2 2095.41   757.1 2113.64   776.8 2124.77
   800.5 2144.61   815.1 2152.02     838 2170.43   860.5 2185.32   883.8 2197.92
   905.4  2200.2   955.1 2229.91   972.8 2233.43   990.9  2242.2  1017.5 2248.79
#Mann= 3 ,-1,0
       0      .1       0   475.5    .045       0     528      .1       0
Bank Sta=475.5,528
XS Rating Curve= 0 ,0
Exp/Cntr(USF)=0,0
Exp/Cntr=0.3,0.1

Type RM Length L Ch R = 1 ,32909   ,763.4,744.6,721.1
XS GIS Cut Line= 2
2177932.34259464630036.4309640962178831.62723304 629514.38861045
#Sta/Elev= 30
       0    2247    41.4 2218.85    54.3 2215.05    78.3 2198.97   133.9 2166.95
   152.4 2153.38   163.2 2149.21   244.9 2098.53   263.4  2084.6   277.4 2081.92
   291.2 2071.88   303.7 2067.08   327.1 2048.24   346.7 2036.31   373.9 2033.12
   391.5 2025.99   434.6 2029.01   448.12026.854   464.6 2025.58   494.62026.555
   546.6 2026.35   596.4 2030.77   663.6 2031.16   698.7 2045.23   787.3 2065.04
   962.1  2132.9   975.7 2133.89  1003.1 2149.56    1022 2150.74  1039.8 2158.68
#Mann= 3 ,-1,0
       0      .1       0   448.1    .045       0   494.6      .1       0
Bank Sta=448.1,494.6
XS Rating Curve= 0 ,0
Exp/Cntr(USF)=0,0
Exp/Cntr=0.3,0.1

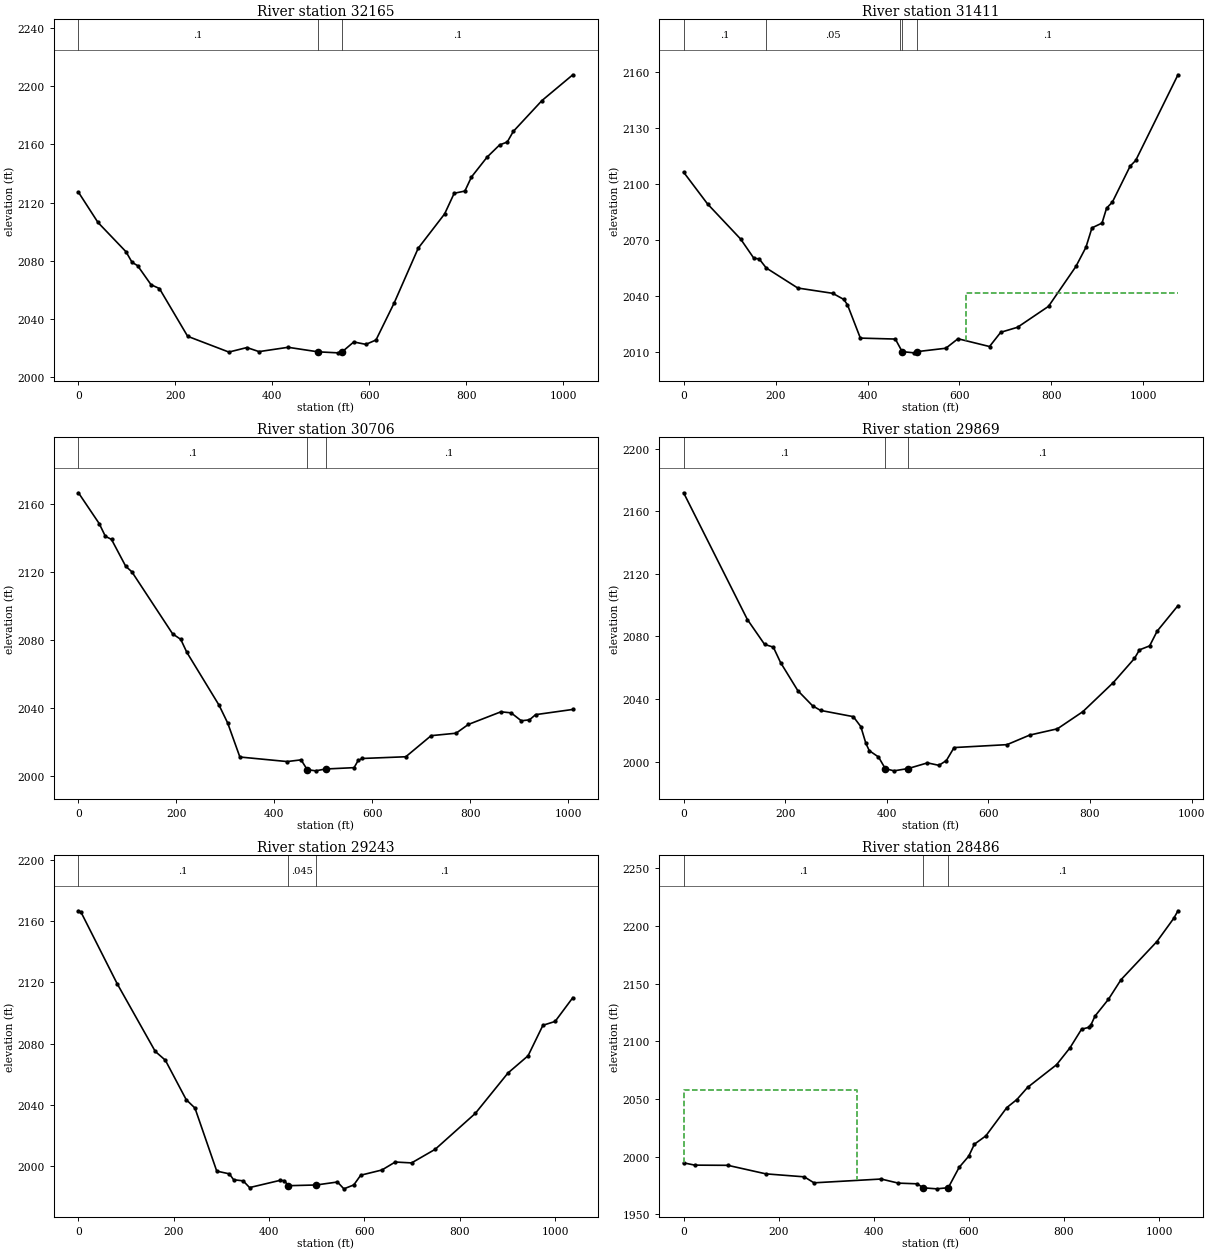
Type RM Length L Ch R = 1 ,32165   ,756.6,753.7,753.1
XS GIS Cut Line= 6
2178753.84384675630581.2621930092178822.54810567630501.575016424
2178881.39017959 630417.771050172178922.88583151630330.468075171
2179093.90484643629738.1920287612179128.39132601629645.694510341
#Sta/Elev= 30
       0  2127.2    40.3 2106.39    98.1 2086.26   110.6    2079     122 2076.72
   149.7 2063.62     167 2060.99   225.2 2028.17   310.2 2017.33   347.4 2020.43
   372.4 2017.64   432.3 2020.61   493.9  2017.5   534.5  2016.8  544.042017.566
   567.8 2024.28   592.8 2022.62   613.6 2025.62   651.1 2051.07   700.6 2088.67
   755.2 2112.31   774.9 2126.47   796.9 2127.98   810.5 2137.66   842.7  2151.3
   868.6 2159.71   884.3 2161.68   896.8 2168.98     956 2190.22  1019.5  2207.9
#Mann= 3 ,-1,0
       0      .1       0   493.9    .045       0  544.04      .1       0
Bank Sta=493.9,544.04
XS Rating Curve= 0 ,0
Exp/Cntr(USF)=0,0
Exp/Cntr=0.3,0.1

Type RM Length L Ch R = 1 ,31411   ,696.1,704.8,710.9
XS GIS Cut Line= 6
2179512.75997984631133.1216535872179485.26561226630582.229054585
2179490.79709725630504.2895779162179506.94404659630408.233339593
2179542.47383118630302.114785418 2179643.2567661 630088.64933309
#Sta/Elev= 30
       0 2106.43      52  2089.4   124.1 2070.51     153 2060.14   164.2 2059.92
   179.7 2055.01   248.3 2044.24   324.4 2041.39   348.4 2038.11   356.4 2035.22
   384.4 2017.35   460.5 2016.84  475.332010.091   501.1 2009.44   508.6 2010.11
   570.3 2011.91   596.7    2017   665.3 2012.83   689.7 2020.47   726.2 2023.16
   793.6  2034.4   853.2 2055.81     875  2066.1   888.1 2076.53     910 2079.11
   919.9  2087.1   932.6 2090.41   971.2  2109.7   983.2 2112.71  1075.2 2158.73
#Mann= 5 ,-1,0
       0      .1       0  178.44     .05       0  471.56      .1       0
  475.33    .045       0   508.6      .1       0
#XS Ineff= 2 , 0
                           615.1         2041.66
Permanent Ineff=
       F       F
Bank Sta=475.33,508.6
XS Rating Curve= 0 ,0
Exp/Cntr(USF)=0,0
Exp/Cntr=0.3,0.1

Type RM Length L Ch R = 1 ,30706   ,807.5,837.5,831.1
XS GIS Cut Line= 2
2180005.26989671631213.8841558952180285.34371417630244.104747116
#Sta/Elev= 30
       0 2166.35    42.4 2148.25    54.9 2140.82    67.5 2138.96    96.5  2123.2
     109 2119.96   192.3 2083.49   208.9 2080.25   221.4  2072.6   287.2 2041.54
   304.7 2031.14   329.6 2011.16   426.1 2008.49   454.6 2009.49     467 2003.78
   484.3 2003.04   504.5 2004.12   562.8 2004.91   571.1 2009.13   579.5  2010.3
   668.4 2011.31   720.1  2023.7     771 2025.14     796 2030.27   862.6 2037.71
   883.4  2037.1   904.2 2032.44   920.9 2032.99   933.4 2036.04  1009.4  2039.1
#Mann= 3 ,-1,0
       0      .1       0     467    .045       0   504.5      .1       0
Bank Sta=467,504.5
XS Rating Curve= 0 ,0
Exp/Cntr(USF)=0,0
Exp/Cntr=0.3,0.1

Type RM Length L Ch R = 1 ,29869   ,628.8,625.8,619
XS GIS Cut Line= 5
2180515.73330113 631469.098870092180604.61074309631362.610285296
2180970.75443918630863.5017860082181037.43442392630778.765406922
 2181101.2400706630692.166826844
#Sta/Elev= 30
       0 2171.78   125.5 2090.77   159.4 2074.87   176.6 2073.11   190.9 2063.24
   224.8 2045.31   253.9 2035.61   269.5 2032.68     334 2028.69   348.8 2022.34
   358.8 2011.57   365.5 2006.93   383.6 2002.91     3971995.436   414.1 1994.05
   442.3 1995.54     480 1999.14   502.6 1997.56   517.2 2000.63   532.4 2008.93
   636.6 2010.79   681.2  2016.9   735.8 2020.92   785.9 2031.89   845.8 2050.47
   887.4 2065.88   897.3 2071.37   917.3 2073.92   932.1 2083.34   973.1 2099.65
#Mann= 3 ,-1,0
       0      .1       0     397    .045       0   442.3      .1       0
Bank Sta=397,442.3
XS Rating Curve= 0 ,0
Exp/Cntr(USF)=0,0
Exp/Cntr=0.3,0.1

Type RM Length L Ch R = 1 ,29243   ,762.8,756.5,733.9
XS GIS Cut Line= 2
2181121.75463845631810.2318080532181573.30222171630876.652416497
#Sta/Elev= 30
       0 2166.71     5.6 2165.65    81.1 2119.18   161.1 2074.93   182.3 2069.18
     226 2043.45   244.4 2037.94   290.1  1996.8   316.6 1995.01   325.5 1991.16
   345.5 1990.44     359 1986.05   421.9 1990.69   432.2 1990.59   439.8 1987.28
   498.8 1987.75   543.3 1989.69   556.8 1985.23   577.6 1987.79   592.1 1994.13
   636.6 1997.53   664.5 2002.73   698.8 2002.15   748.3 2011.03   832.4 2034.44
     901 2060.83   943.2 2072.09   974.3 2091.97   999.9 2094.49    1037 2110.01
#Mann= 3 ,-1,0
       0      .1       0   439.8    .045       0   498.8      .1       0
Bank Sta=439.8,498.8
XS Rating Curve= 0 ,0
Exp/Cntr(USF)=0,0
Exp/Cntr=0.3,0.1

Type RM Length L Ch R = 1 ,28486   ,697.1,748.9,782.6
XS GIS Cut Line= 6
2181899.54916951631909.5400482572181972.86562392631814.070422918
2182029.81531318631720.9521708342182048.66960618631628.390020013
2182074.44153626631203.369216502 2182115.5726876 630916.52891092
#Sta/Elev= 30
       0 1994.58    23.5 1992.58      93 1992.42     173 1985.02   253.8 1982.43
   274.2 1977.24   415.5 1980.53   451.5 1976.98   491.6 1976.37   503.6 1972.92
   532.2 1972.02  556.621973.007   579.6  1990.7   599.6  2000.3   611.6 2010.74
   635.7 2017.97   679.8 2042.52     701 2049.51   723.5 2060.05   784.5 2079.72
   812.8 2094.44     837 2110.51     853 2112.19   856.5 2114.06   865.3  2121.9
   893.6 2136.48     920 2153.47   995.5 2186.56    1031 2206.76  1039.8 2213.25
#Mann= 3 ,-1,0
       0      .1       0   503.6    .045       0  556.62      .1       0
#XS Ineff= 2 , 0
          365.68 2057.98
Permanent Ineff=
       F       F
Bank Sta=503.6,556.62
XS Rating Curve= 0 ,0
Exp/Cntr(USF)=0,0
Exp/Cntr=0.3,0.1

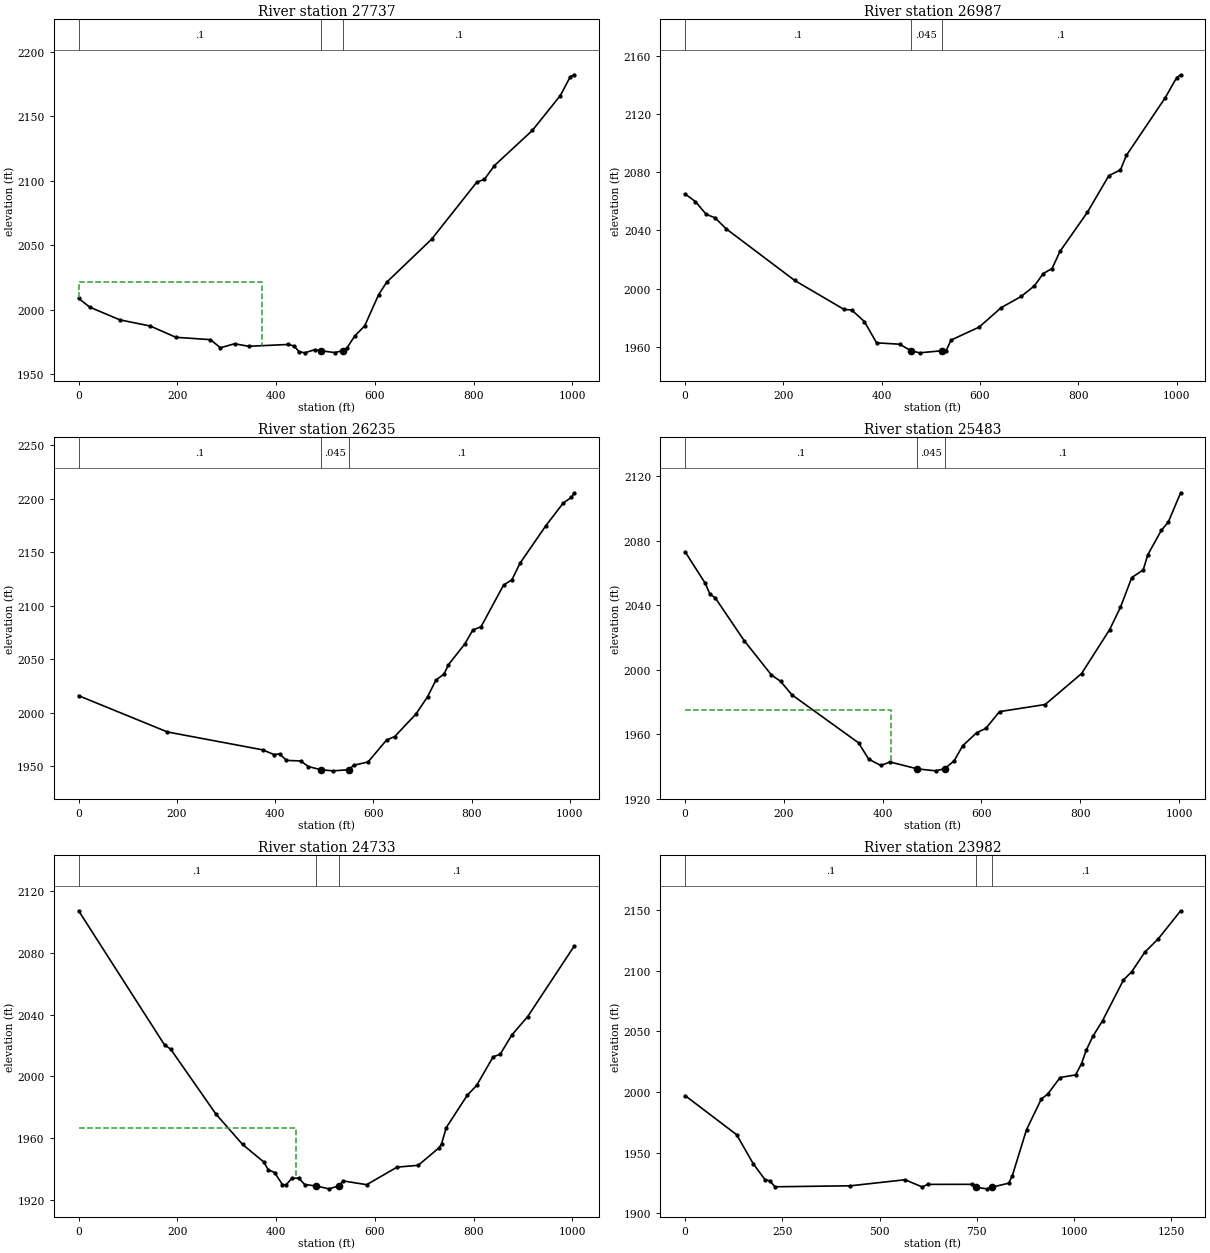
Type RM Length L Ch R = 1 ,27737   ,784.4,750.1,721.4
XS GIS Cut Line= 6
  2181934.342407632042.7520521732182030.90881492632022.848876759
2182126.16551417632004.7773905842182304.26227084631970.117683008
  2182378.215535631957.5232200032182923.85716026631876.921675175
#Sta/Elev= 30
       0 2008.66    22.3 2001.86    83.6 1991.94   144.7 1987.21   196.9 1978.42
   266.9 1976.59   287.3 1970.26   315.8 1973.41   344.3 1971.44   424.6 1972.86
   436.7 1971.61   445.9 1967.37     458 1966.35   478.2  1968.8   490.4 1967.98
   518.7 1966.56   534.9 1968.06   542.9 1969.88   559.1 1979.35   579.3 1987.26
   607.6 2011.56   623.8 2021.15   714.9 2054.59   806.3 2098.83   821.9 2101.12
   842.2 2111.78   918.9 2139.03   975.6 2166.15   995.8 2180.81  1003.6 2182.25
#Mann= 3 ,-1,0
       0      .1       0   490.4    .045       0   534.9      .1       0
#XS Ineff= 2 , 0
          370.96 2021.12
Permanent Ineff=
       F       F
Bank Sta=490.4,534.9
XS Rating Curve= 0 ,0
Exp/Cntr(USF)=0,0
Exp/Cntr=0.3,0.1

Type RM Length L Ch R = 1 ,26987   ,720.9,751.8,775.9
XS GIS Cut Line= 6
2182513.57845326632984.0556157532182557.20336601 632894.48558493
2182633.59986676632719.0161195842182672.94362009632640.857811332
2182913.73644559632170.8210217512182979.78388567632093.552147418
#Sta/Elev= 30
       0 2065.04      21 2059.82      43 2051.02    60.7 2048.73    83.3 2041.19
   223.1 2005.64   323.4 1985.77     339 1985.38   364.7 1977.48   389.6 1962.84
   436.6 1961.89     459 1957.52     477 1955.97     522 1957.39     531 1957.32
   541.2 1964.74   598.4 1973.67   643.3 1987.02   683.8 1994.67   710.6 2001.88
   728.7 2010.38   746.7 2013.86   762.8 2025.61   818.6 2052.49   862.1 2077.55
   885.9  2081.6   897.8 2091.46   977.2 2131.24  1000.3 2144.97  1008.3 2146.86
#Mann= 3 ,-1,0
       0      .1       0     459    .045       0     522      .1       0
Bank Sta=459,522
XS Rating Curve= 0 ,0
Exp/Cntr(USF)=0,0
Exp/Cntr=0.3,0.1

Type RM Length L Ch R = 1 ,26235   ,758.4,752.9,743.7
XS GIS Cut Line= 6
2182811.63330334633185.252719924   2182899.76961633132.250529334
2182989.03255484633091.5032355042183234.02878401633016.397414595
2183401.34373809632965.1061785822183761.36860859632854.737632915
#Sta/Elev= 30
       0 2015.72   180.9 1981.79   375.1 1965.04   397.5 1960.69   409.3 1961.25
   423.1 1955.22   451.9 1954.68   467.9 1949.48   492.9 1946.46     518 1945.45
  549.841946.486   559.9 1950.65   589.2 1953.75   626.8 1974.26   643.5 1977.53
   686.6 1998.54   710.5 2014.79   727.3 2030.32     744 2036.04   752.9 2044.74
   785.8 2063.91   802.5 2077.06   819.3 2080.28     865 2119.17     882  2124.1
   898.8 2139.83   951.4 2174.86   986.5 2195.89  1003.3 2201.23  1008.8 2205.51
#Mann= 3 ,-1,0
       0      .1       0   492.9    .045       0  549.84      .1       0
Bank Sta=492.9,549.84
XS Rating Curve= 0 ,0
Exp/Cntr(USF)=0,0
Exp/Cntr=0.3,0.1

Type RM Length L Ch R = 1 ,25483   ,749.2,750,745.9
XS GIS Cut Line= 6
2183168.56434801633916.9205479172183254.22657825633868.215592846
2183338.00068893 633819.551648172183495.04171342633729.055110008
2183646.66969101633641.6822532562184037.92054893633416.224042758
#Sta/Elev= 30
       0  2073.1      41 2053.46    50.2 2046.89    61.1 2044.52   119.7 2017.96
   174.8 1996.71   193.3 1992.76   216.3 1984.37   351.1 1954.61   371.6 1944.48
   396.4 1940.56   414.9 1942.72   470.3 1938.45   507.2 1937.23   525.7 1938.57
   544.7 1943.49   561.9 1952.76   590.3 1960.88   608.8 1963.56   636.5 1973.96
   728.9 1978.37   802.7 1997.59   859.5 2024.85   881.2  2038.6   904.3 2057.12
   927.4 2061.86   936.8 2071.33   964.3  2086.5   978.1 2091.48  1003.2 2109.71
#Mann= 3 ,-1,0
       0      .1       0   470.3    .045       0   525.7      .1       0
#XS Ineff= 2 , 0
          417.16 1974.96
Permanent Ineff=
       F       F
Bank Sta=470.3,525.7
XS Rating Curve= 0 ,0
Exp/Cntr(USF)=0,0
Exp/Cntr=0.3,0.1

Type RM Length L Ch R = 1 ,24733   ,764.3,751,730.9
XS GIS Cut Line= 6
2183580.06680584634557.3484009212183663.07746659634504.441354498
2183897.61669567634354.9590419232184045.19153176634260.902471513
2184342.97702542634071.1098720882184419.31348692634007.731061846
#Sta/Elev= 30
       0  2107.4     174 2020.38   186.4 2017.63   278.3 1975.44   332.2 1955.76
   374.9 1944.46   384.3 1939.32   397.1 1937.53   412.8 1929.77   420.3 1929.58
   431.8  1933.8     446 1933.95   457.9 1929.79  480.611928.876   507.2 1926.98
   526.6 1928.85   536.1 1932.09   583.6 1929.68   645.2 1941.08   687.9 1942.23
   730.6 1953.75   735.3 1956.29   744.8 1966.74   787.5 1987.77   806.5 1994.17
   839.7 2012.65   853.9 2014.26   877.6  2026.8   909.8 2038.77  1003.9 2084.45
#Mann= 3 ,-1,0
       0      .1       0  480.61    .045       0   526.6      .1       0
#XS Ineff= 2 , 0
          440.92 1966.49
Permanent Ineff=
       F       F
Bank Sta=480.61,526.6
XS Rating Curve= 0 ,0
Exp/Cntr(USF)=0,0
Exp/Cntr=0.3,0.1

Type RM Length L Ch R = 1 ,23982   ,918.4,926.5,931.6
XS GIS Cut Line= 6
2184306.67983344635320.8785121652184438.28785843634978.211404338
2184584.03034909634656.5476775912184653.61157475634495.671030834
2184690.83656593634415.8122666782184818.12043209634154.447303832
#Sta/Elev= 30
       0 1997.11   132.5 1964.89   175.4 1940.88   205.4 1927.91   218.2 1926.82
   231.1    1922   425.3 1922.81   565.7 1927.78   609.7 1921.86   623.6 1923.97
     737 1924.01 747.2481921.604   776.2  1920.3 788.1781921.575   832.4 1924.99
   841.5 1931.18     878 1969.06   915.9 1994.19   932.4 1998.34   964.4 2011.99
  1004.3 2014.14  1019.5 2023.49  1031.5 2034.46  1048.7 2045.94  1073.4 2058.71
  1127.3 2092.31  1148.2 2098.97  1182.2 2115.16    1217 2126.32  1274.3 2149.29
#Mann= 3 ,-1,0
       0      .1       0 747.248    .045       0 788.178      .1       0
Bank Sta=747.248,788.178
XS Rating Curve= 0 ,0
Exp/Cntr(USF)=0,0
Exp/Cntr=0.3,0.1

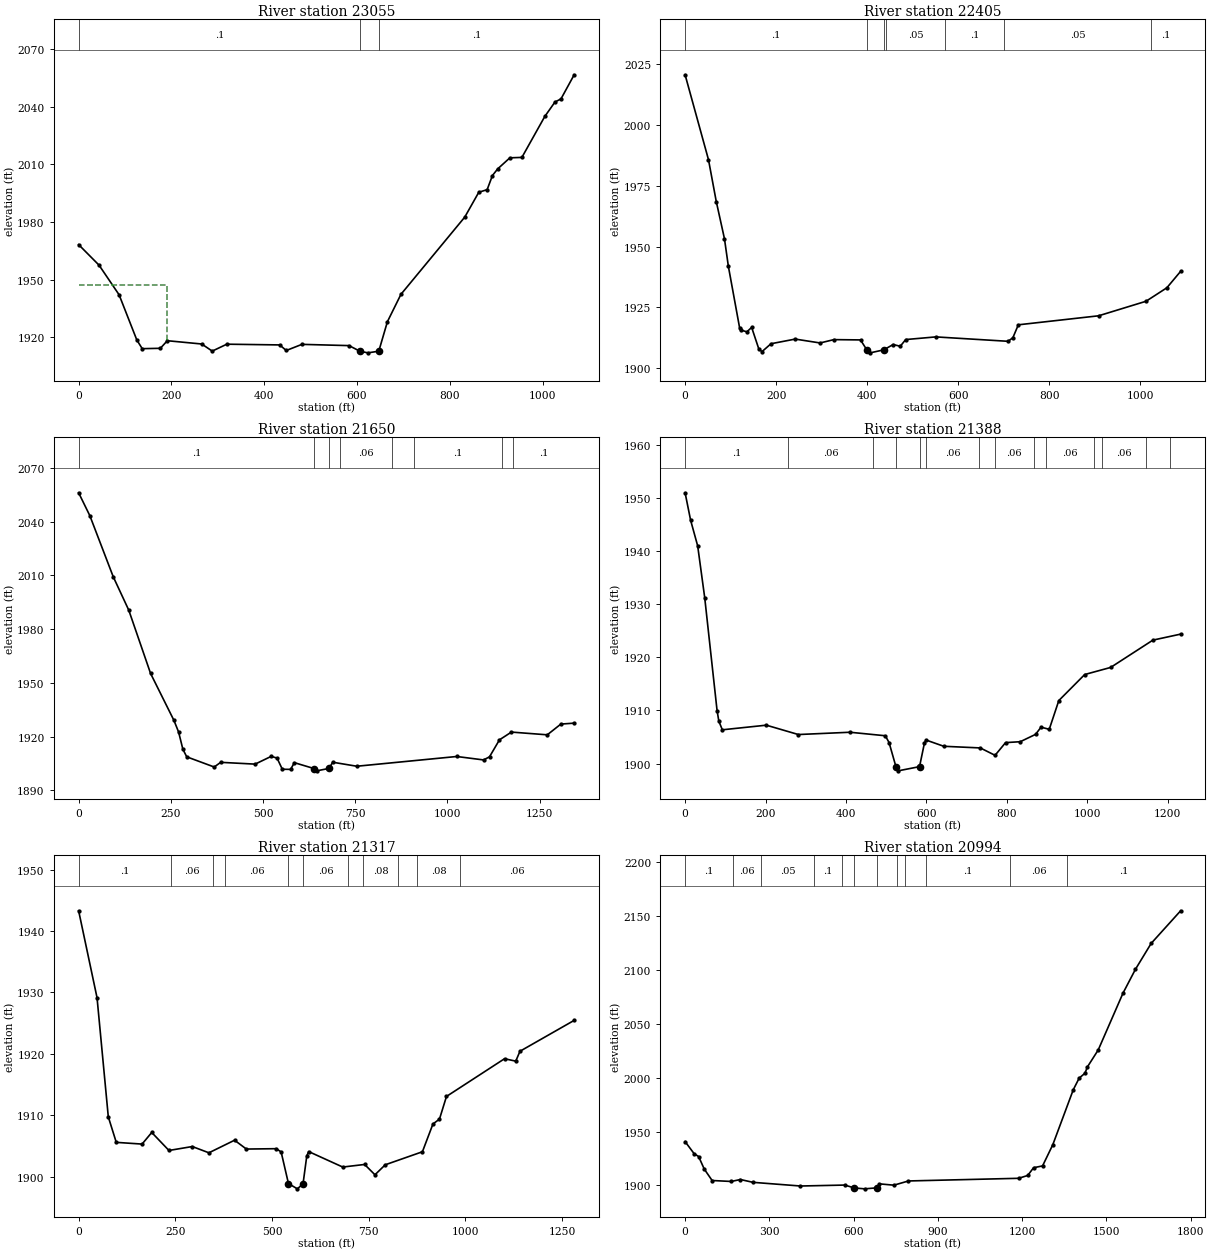
Type RM Length L Ch R = 1 ,23055   ,646.8,650.6,649.8
XS GIS Cut Line= 2
2184978.35092725635599.8074931462185637.72609434 634759.40832206
#Sta/Elev= 30
       0 1968.19      44  1957.5    87.2  1942.1   125.4 1918.59   137.1 1914.05
   176.2 1914.24   191.2 1918.19   265.3 1916.48     288 1912.78   319.4 1916.38
   433.4    1916   447.6  1913.1   481.3 1916.29   582.9 1915.64  606.571912.693
   623.6 1911.88     647 1912.73   665.6 1928.08   694.8 1942.33   832.4 1982.52
   862.6 1995.44   880.6 1996.78     892 2004.14   903.4 2007.61   929.6 2013.35
   955.5 2013.57  1004.9 2034.88  1026.8 2042.39  1039.8 2044.02  1068.2 2056.56
#Mann= 3 ,-1,0
       0      .1       0  606.57    .045       0     647      .1       0
#XS Ineff= 2 , 0
           190.1 1947.38
Permanent Ineff=
       F       F
Bank Sta=606.57,647
XS Rating Curve= 0 ,0
Exp/Cntr(USF)=0,0
Exp/Cntr=0.3,0.1

Type RM Length L Ch R = 1 ,22405   ,745.8,754.6,752.9
XS GIS Cut Line= 4
2185477.26983715635926.0424149722185548.92274152635827.681184571
2185958.81142212635359.4886373892185862.48502654635028.066492316
#Sta/Elev= 30
       0  2020.6    51.4 1985.72    68.5 1968.53    86.5 1953.25    95.1  1941.9
   119.8 1916.63   122.9 1915.71   135.7 1914.98   146.3 1916.79   162.2 1907.84
   169.1 1906.86   188.8 1910.09     242    1912   296.7 1910.41     327 1911.78
   385.5 1911.66  399.281907.602   406.8 1906.35   436.3 1907.56   457.4 1909.77
   472.8 1909.04   484.9 1911.81     551  1912.9   709.8 1911.09   720.4 1912.57
   732.4 1917.87   908.8 1921.57    1013 1927.54  1058.8 1933.08  1089.1 1939.84
#Mann= 7 ,-1,0
       0      .1       0  399.28    .045       0   436.3      .1       0
  441.69     .05       0  571.69      .1       0  701.69     .05       0
 1023.96      .1       0
Bank Sta=399.28,436.3
XS Rating Curve= 0 ,0
Exp/Cntr(USF)=0,0
Exp/Cntr=0.3,0.1

Type RM Length L Ch R = 1 ,21650   ,262.2,262.1,260.9
BEGIN DESCRIPTION:
Structure XS 4
END DESCRIPTION:
XS GIS Cut Line= 3
 2185823.3795444636254.9371762762186096.86612166636162.207329962
2186878.13805491635452.947508613
#Sta/Elev= 30
       0 2056.11    30.4 2043.32    93.8 2009.24     136 1990.56   195.1 1955.24
   258.5 1929.01   271.2 1922.49   282.7 1912.92   293.2 1908.67   367.7 1902.99
   385.3  1905.6   478.7  1904.6   522.4 1908.94   538.2 1907.96   552.4 1901.74
     575 1901.66     585 1905.42     639 1902.09   645.8 1900.85  679.431902.219
     689 1905.66   754.5 1903.42  1025.5 1908.86  1098.2 1906.94  1114.4 1908.69
  1141.4 1918.17  1173.8 1922.49  1271.1 1920.96  1307.9 1926.96    1344 1927.48
#Mann= 8 ,-1,0
       0      .1       0     639    .045       0  679.43      .1       0
  708.78     .06       0  848.78     .05       0  908.78      .1       0
 1148.78     .05       0 1178.78      .1       0
Bank Sta=639,679.43
XS Rating Curve= 0 ,0
Exp/Cntr(USF)=0,0
Exp/Cntr=0.3,0.1

Type RM Length L Ch R = 1 ,21388   ,65.9,70.4,77.8
BEGIN DESCRIPTION:
Structure XS 3
END DESCRIPTION:
XS GIS Cut Line= 5
 2186031.6428383636371.6761775442186193.21953034636299.245246629
2186459.26391121 636176.66982508  2186719.736682635948.233812194
2186964.88752509635612.544305452
#Sta/Elev= 30
       0 1950.94    13.7 1945.78    31.3 1940.94    48.8 1931.19    79.5 1909.97
    83.9 1907.97    92.6 1906.35     202 1907.22   281.6 1905.46     410 1905.89
   497.8 1905.23   507.1 1903.96   524.4 1899.36   529.7 1898.63   582.9 1899.42
     595 1903.83   598.9 1904.43   643.2 1903.25   733.9 1902.94   770.7 1901.55
   796.8 1903.94   833.3 1904.11   871.4 1905.49     885 1906.85   905.4 1906.44
   929.2 1911.85   993.6 1916.75    1058 1918.08  1163.1 1923.22  1232.1 1924.35
#Mann= 14 ,-1,0
       0      .1       0  257.07     .06       0  467.07      .1       0
   524.4    .045       0   582.9      .1       0  599.99     .06       0
  729.99     .08       0  769.99     .06       0  866.44     .08       0
  896.44     .06       0 1016.44      .1       0 1036.44     .06       0
 1146.44     .05       0 1206.44     .06       0
Bank Sta=524.4,582.9
XS Rating Curve= 0 ,0
Exp/Cntr(USF)=0,0
Exp/Cntr=0.3,0.1

Type RM Length L Ch R = 1 ,21317   ,298,323.7,339.9
BEGIN DESCRIPTION:
Structure XS 2
END DESCRIPTION:
XS GIS Cut Line= 6
2186034.42864334636403.7129354492186215.50597063636352.175542298
2186478.76454645636236.5646333372186618.05479821636139.061457105
2186760.13085501636013.7002305212187027.56813839635657.117186015
#Sta/Elev= 30
       0 1943.29    47.6 1929.13    76.7 1909.72    97.3 1905.57     164 1905.29
     189 1907.18   233.5 1904.25   293.8 1904.89   336.8 1903.87   403.1 1905.92
   433.6 1904.48   510.8 1904.54   523.5 1904.01   542.4 1898.86   565.4    1898
   580.1 1898.82   589.8 1903.36   594.7 1904.07   682.7 1901.55   739.3 1901.97
     766 1900.29   792.7 1901.92   888.7 1904.04   915.9 1908.56   932.8 1909.36
   950.9 1913.05  1100.9 1919.19    1130  1918.8  1140.9 1920.41    1281 1925.44
#Mann= 11 ,-1,0
       0      .1       0  238.27     .06       0  348.27     .05       0
  378.27     .06       0   542.4    .045       0   580.1     .06       0
  695.82      .1       0  735.82     .08       0  825.82     .06       0
   875.3     .08       0   985.3     .06       0
Bank Sta=542.4,580.1
XS Rating Curve= 0 ,0
Exp/Cntr(USF)=0,0
Exp/Cntr=0.3,0.1

Type RM Length L Ch R = 1 ,20994   ,844.3,881.8,877
BEGIN DESCRIPTION:
Structure XS 1
END DESCRIPTION:
XS GIS Cut Line= 6
2185996.81335464636486.3222181112186446.96920851636482.304196671
2186534.53858717636482.8353635822186609.56107493636482.209708676
2187256.30015134 636460.576061392187723.14119609636716.543998701
#Sta/Elev= 30
       0 1940.63    32.1 1929.41    48.1 1926.76    68.2  1915.1    96.2 1904.47
   164.3 1903.58   196.9 1905.39   241.9 1902.77   410.7 1899.36   568.2 1900.23
   602.7 1897.55   639.1 1896.73   683.1 1897.66   691.1 1901.37   743.2 1900.13
   795.2 1904.05  1187.4 1906.52  1219.6 1909.16  1240.5 1916.35  1272.5 1918.03
    1309 1937.76  1381.9 1988.85  1402.8 1999.61  1423.4 2004.13  1432.2 2010.04
  1470.6 2025.75  1558.9 2078.59  1603.1  2100.7  1659.1 2124.76    1764 2155.07
#Mann= 12 ,-1,0
       0      .1       0     170     .06       0     270     .05       0
  460.17      .1       0  557.74     .08       0   602.7    .045       0
   683.1     .08       0  752.77      .1       0  782.77     .08       0
  857.77      .1       0 1155.89     .06       0 1359.87      .1       0
Bank Sta=602.7,683.1
XS Rating Curve= 0 ,0
Exp/Cntr(USF)=0,0
Exp/Cntr=0.3,0.1