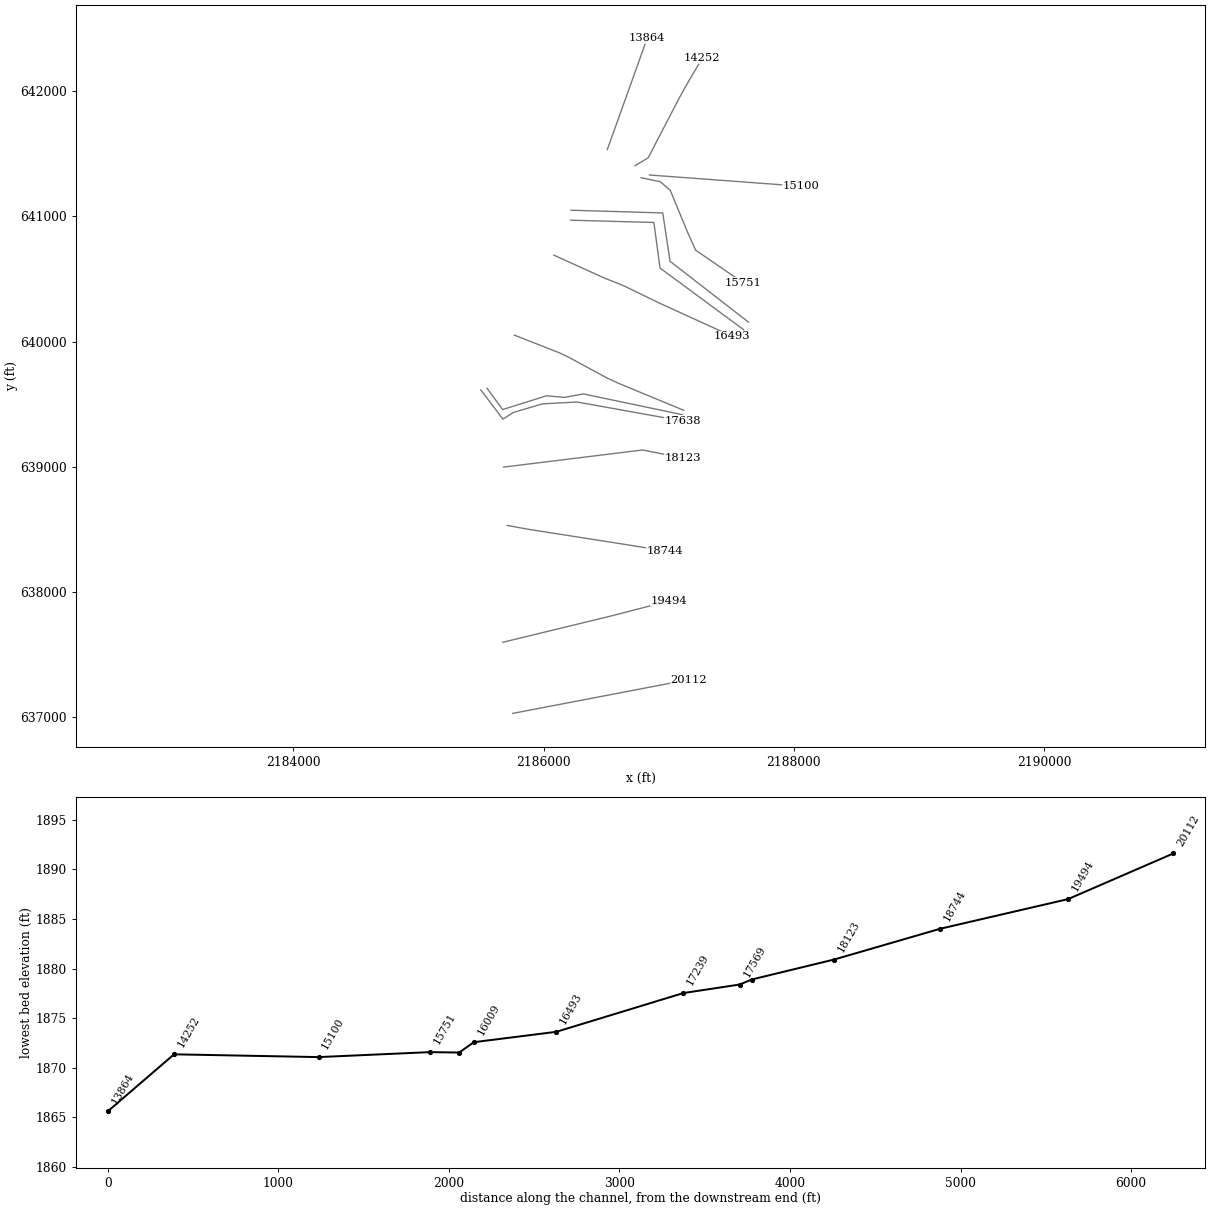
HEC-RAS study RFBUCKRV.prj: RFBUCKRV

--- RFBUCKRV.g01 (geometry) --- (continued)

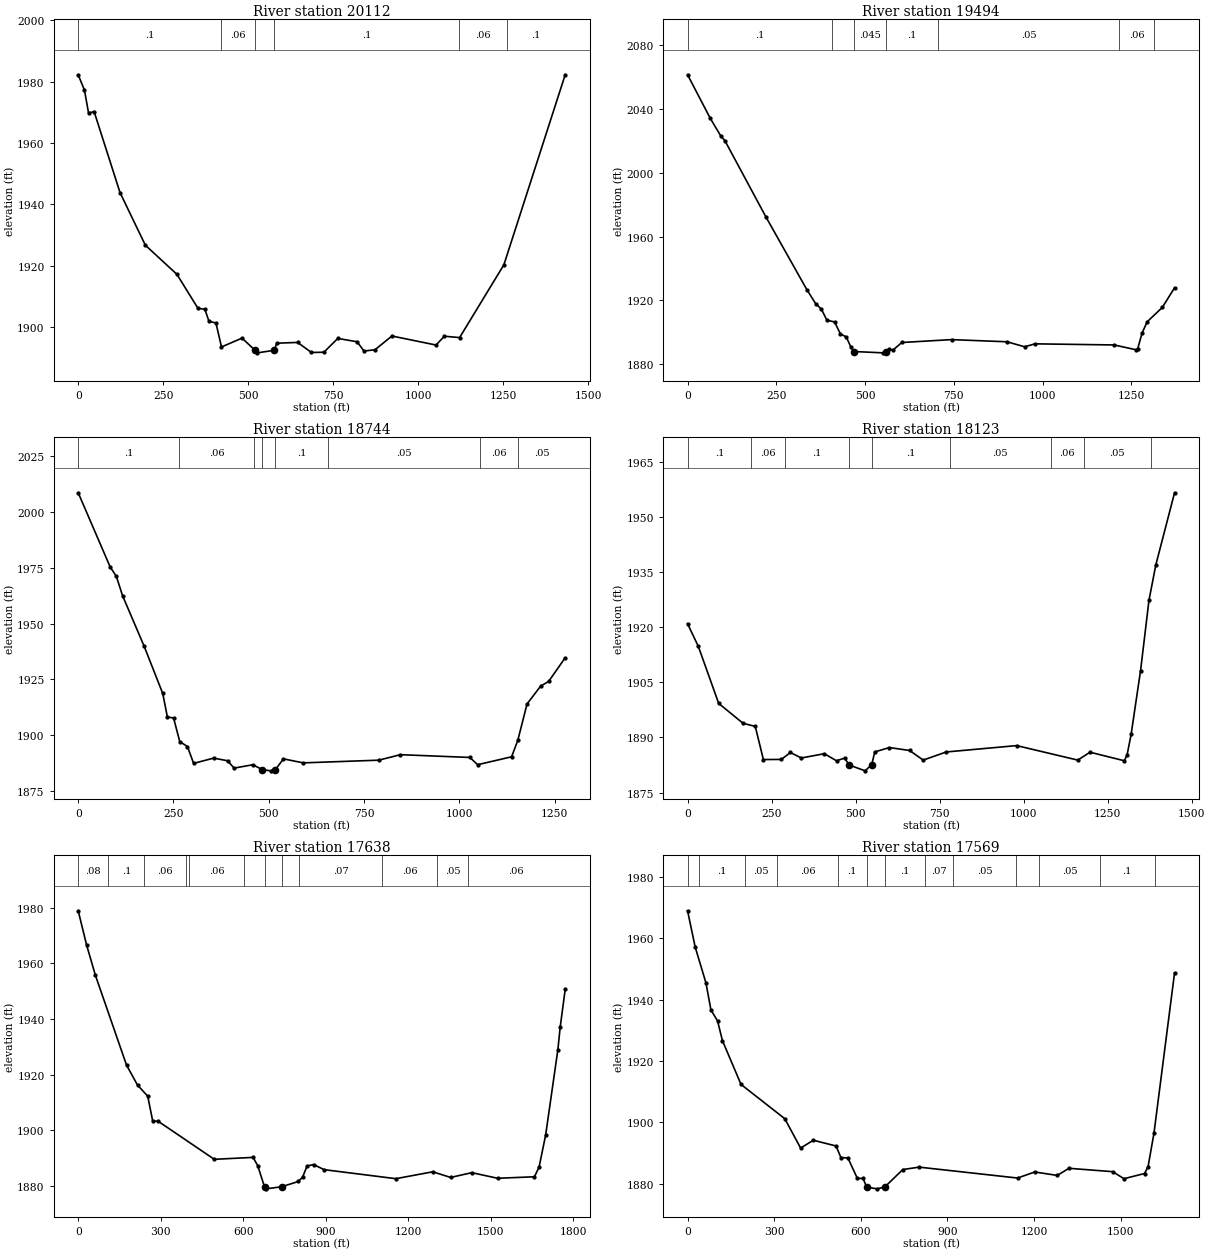
Type RM Length L Ch R = 1 ,20112   ,613.3,618.2,615.3
XS GIS Cut Line= 2
2185754.23534471637027.174511049 2187161.2607402637296.721897366
#Sta/Elev= 30
       0 1982.22    18.3 1977.29    30.5 1969.78    46.8 1970.26     123 1943.85
   197.5 1926.71   290.5 1917.19   352.2 1906.14   372.6 1905.81   384.8 1901.86
   405.2 1901.36   421.5 1893.52   481.9 1896.41  519.46 1892.52   527.4 1891.61
   576.2 1892.43   584.4 1894.76   645.5    1895   686.2 1891.73   722.8 1891.81
   763.6 1896.31   820.6 1895.22   840.8 1892.18   873.5 1892.64   922.8  1897.1
  1052.7 1894.15  1077.2 1897.02    1122 1896.58  1252.3 1920.32  1432.6 1982.26
#Mann= 6 ,-1,0
       0      .1       0     420     .06       0  519.46    .045       0
   576.2      .1       0    1120     .06       0    1260      .1       0
Bank Sta=519.46,576.2
XS Rating Curve= 0 ,0
Exp/Cntr(USF)=0,0
Exp/Cntr=0.3,0.1

Type RM Length L Ch R = 1 ,19494   ,763.2,750,729.6
XS GIS Cut Line= 6
2185673.85756576637595.4538732622185954.73758142637663.745403335
2186112.63752809637702.1357465092186458.80284625 637786.29994826
 2186552.9358601637809.1863854232187004.83365345 637926.65634453
#Sta/Elev= 30
       0 2061.52    64.1 2034.13    92.9 2023.35   105.3 2020.11   220.6 1972.33
   335.8 1926.74   360.5 1917.95     377  1914.4   392.4 1907.47     414 1906.41
   430.5 1898.87     447 1896.98   460.3 1890.44  469.571887.815   549.9    1887
   558.1 1887.76   566.3 1889.24   578.7 1888.76   603.4 1893.49   743.4  1895.3
   899.8 1893.94   949.4 1890.79   978.3 1892.65  1201.5 1891.95  1263.5 1888.92
  1267.6 1889.38    1280 1899.32  1294.4 1906.47  1337.1  1915.5  1371.6 1927.83
#Mann= 7 ,-1,0
       0      .1       0  406.56     .07       0  469.57    .045       0
   558.1      .1       0  706.56     .05       0 1214.69     .06       0
 1314.69      .1       0
Bank Sta=469.57,558.1
XS Rating Curve= 0 ,0
Exp/Cntr(USF)=0,0
Exp/Cntr=0.3,0.1

Type RM Length L Ch R = 1 ,18744   ,612,621.2,625.8
XS GIS Cut Line= 6
2185709.82829434638529.9946550882185806.59516117638511.659718007
2185902.04871042638495.0400005882186155.22471325638455.468557417
2186602.91443467638385.4949440962186971.03666773638326.130999581
#Sta/Elev= 30
       0 2008.62    83.8  1975.4   100.1 1971.15   116.3 1962.53   173.2 1939.76
   221.8 1918.67     234 1908.13   250.2  1907.7   266.4 1897.13   286.6 1894.89
   302.8 1887.35   355.4 1889.71   391.9 1888.53   408.9 1885.23     458 1886.74
  483.311884.538   505.2 1884.01   517.4 1884.56   538.5 1889.38   590.2 1887.58
   788.6 1888.79   845.3 1891.25  1027.6 1890.01  1047.8 1886.76    1137  1890.3
  1153.2 1897.62  1177.5 1913.96  1213.2 1921.99  1234.2 1924.07  1277.6 1934.69
#Mann= 8 ,-1,0
       0      .1       0  265.38     .06       0  461.63      .1       0
  483.31    .045       0   517.4      .1       0  656.63     .05       0
 1054.75     .06       0 1154.75     .05       0
Bank Sta=483.31,517.4
XS Rating Curve= 0 ,0
Exp/Cntr(USF)=0,0
Exp/Cntr=0.3,0.1

Type RM Length L Ch R = 1 ,18123   ,490.3,484.8,478.6
BEGIN DESCRIPTION:
Structure XS 4
END DESCRIPTION:
XS GIS Cut Line= 3
2185680.29816967638996.024562925 2186790.5306286639132.787515454
2187114.81118259639069.232727461
#Sta/Elev= 30
       0 1920.91    32.1 1914.72    92.6 1899.24   165.1 1893.84   201.4 1892.99
   225.6 1883.98   278.9 1884.01   306.2  1885.9   338.4  1884.4   406.9 1885.57
   443.2 1883.65   467.4 1884.38  480.651882.501   528.4 1880.91     548 1882.61
   557.1 1886.06   600.4 1887.24   660.8 1886.44   701.1 1883.83   769.7 1886.04
   979.2 1887.77  1161.1 1883.83  1197.7 1885.97  1299.6 1883.65  1307.8 1885.21
    1320 1890.89    1348 1908.18    1373 1927.27  1393.4  1936.9  1449.1  1956.5
#Mann= 9 ,-1,0
       0      .1       0     190     .06       0     290      .1       0
  480.65    .045       0     548      .1       0     780     .05       0
    1080     .06       0 1178.62     .05       0 1378.62     .06       0
Bank Sta=480.65,548
XS Rating Curve= 0 ,0
Exp/Cntr(USF)=0,0
Exp/Cntr=0.3,0.1

Type RM Length L Ch R = 1 ,17638   ,71,68.6,69.6
BEGIN DESCRIPTION:
Structure XS 3
END DESCRIPTION:
XS GIS Cut Line= 6
2185498.38213064639613.3438465452185674.75804692639379.645757481
2185758.53660715639432.5585323632185990.76489691639501.639099571
2186268.55696504639516.3370925942187110.00311368639364.819187794
#Sta/Elev= 30
       0  1978.9    30.3 1966.66    62.7 1955.64   175.6 1923.41   215.6 1916.21
   252.7 1912.22   270.8  1903.3   290.9 1903.18   494.7 1889.51   635.6  1890.2
   652.5 1887.27  677.47 1879.54   683.7 1878.89   739.91879.651   800.1 1881.53
     816 1883.16   832.1 1887.13   855.8 1887.61   894.1 1885.79  1154.7 1882.54
  1288.8 1885.02  1353.9 1882.99  1430.9 1884.71  1524.6 1882.69  1658.7 1883.23
  1675.4 1886.75  1699.1 1898.12  1743.7 1928.93  1752.2  1937.1  1770.3 1950.59
#Mann= 12 ,-1,0
       0     .08       0     110      .1       0     240     .06       0
  391.87     .05       0  401.87     .06       0  603.95     .05       0
  677.47    .045       0   739.9     .06       0  804.17     .07       0
 1105.31     .06       0 1305.31     .05       0 1415.31     .06       0
Bank Sta=677.47,739.9
XS Rating Curve= 0 ,0
Exp/Cntr(USF)=0,0
Exp/Cntr=0.3,0.1

Type RM Length L Ch R = 1 ,17569   ,343,330.3,313.7
BEGIN DESCRIPTION:
Structure XS 2
END DESCRIPTION:
XS GIS Cut Line= 6
2185548.35530692639626.5720402662185673.28824762  639456.0753212
2186024.57028086639566.3102688722186165.67101388639553.082075151
2186318.53014132639581.0082618952187109.97096951639414.773995977
#Sta/Elev= 30
       0 1968.95    26.5  1957.1    63.8 1945.43    80.9 1936.67   103.9 1933.08
   120.7 1926.68   185.2 1912.39   336.6 1901.25   391.7 1891.66   435.7 1894.22
   514.5 1892.34   531.1 1888.58   555.6 1888.45   588.1 1881.81   608.2 1881.76
   620.3 1878.97   656.4 1878.39  682.761878.955   745.6 1884.67   802.1 1885.46
  1143.1 1881.91  1202.9 1883.88  1280.6 1882.76  1321.5 1885.08  1472.7 1883.98
  1511.9 1881.69  1583.1 1883.38  1595.3 1885.58  1615.8 1896.49  1687.1  1948.7
#Mann= 13 ,-1,0
       0     .08       0      40      .1       0     200     .05       0
  311.37     .06       0  520.49      .1       0   620.3    .045       0
  682.76      .1       0  823.17     .07       0  918.36     .05       0
 1138.36     .06       0 1218.36     .05       0 1428.36      .1       0
 1618.36     .06       0
Bank Sta=620.3,682.76
XS Rating Curve= 0 ,0
Exp/Cntr(USF)=0,0
Exp/Cntr=0.3,0.1

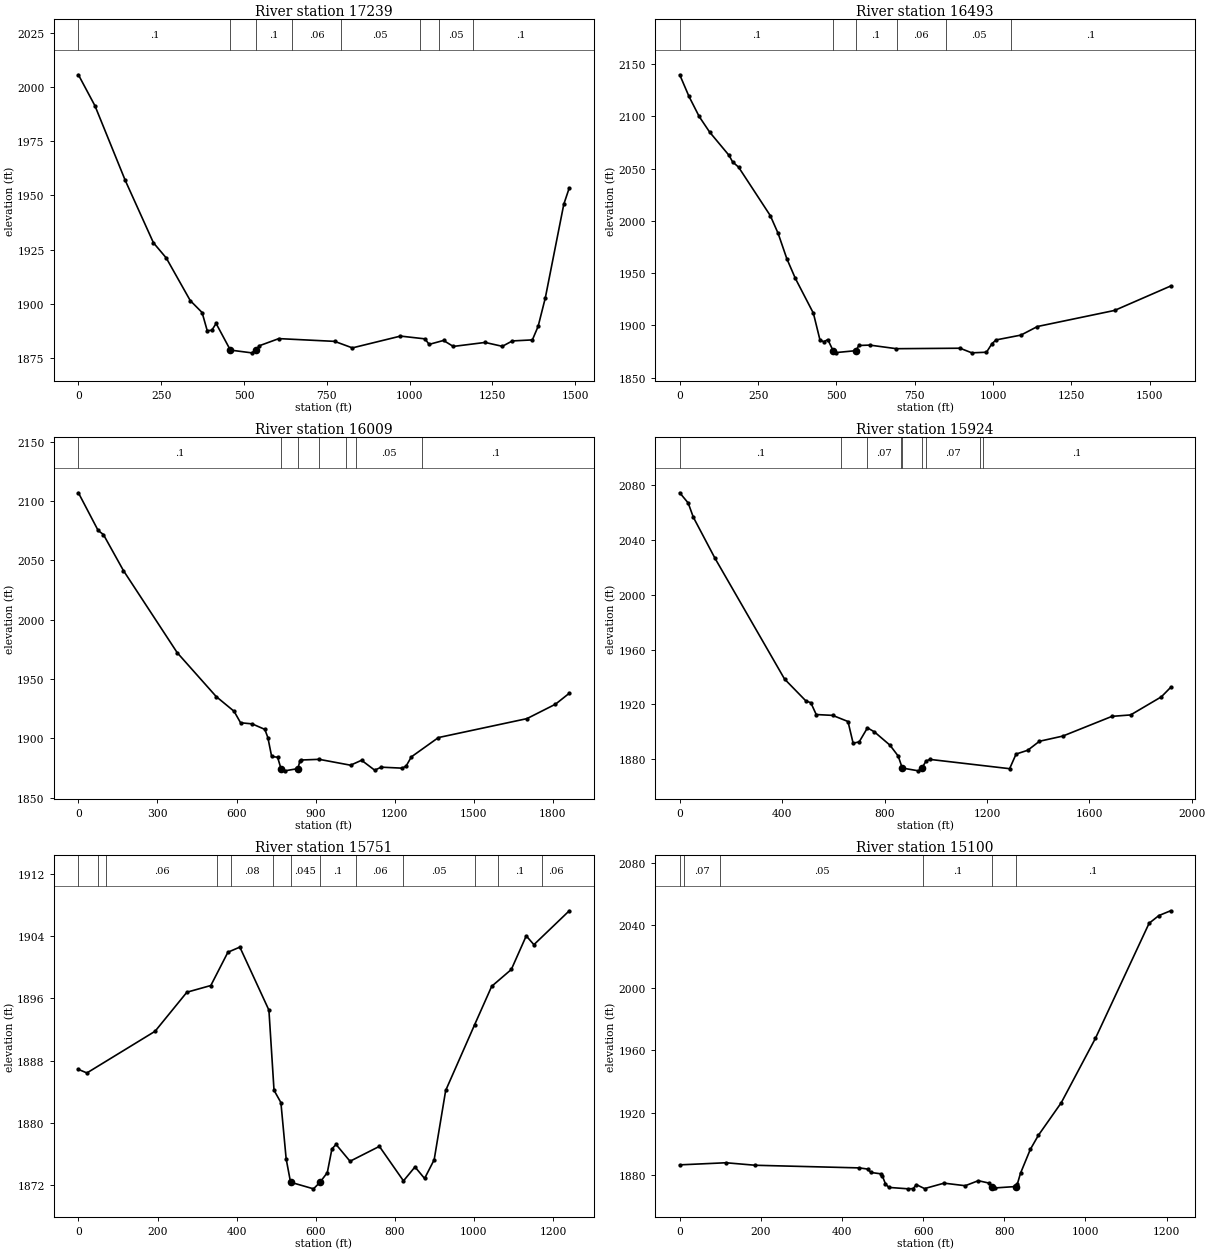
Type RM Length L Ch R = 1 ,17239   ,727.6,745.6,733.6
BEGIN DESCRIPTION:
Structure XS 1
END DESCRIPTION:
XS GIS Cut Line= 6
2185765.96007185640051.2127412562186124.14833184 639910.49648726
2186192.55370684639878.4253571782186505.86804084639708.868609667
2186599.74670247639665.4234573912187118.96020291639450.467218653
#Sta/Elev= 30
       0 2005.55      50 1991.27   141.3 1956.98   226.6 1928.19   265.1 1921.24
   337.8 1901.57   373.5 1896.09   388.9 1887.77   402.6 1887.89   415.8 1891.04
  458.861878.796   522.8 1877.53     537 1878.77     546 1880.78   605.2 1884.08
   773.7 1882.81   827.2 1879.81   972.5 1885.24  1046.1 1883.97  1059.1 1881.43
  1102.4 1883.23  1131.9 1880.48    1228 1882.32  1279.9 1880.53  1310.2 1883.01
  1370.7 1883.49  1388.1 1889.74  1409.8 1902.86  1465.6 1945.96  1482.1 1953.47
#Mann= 8 ,-1,0
       0      .1       0  458.86    .045       0     537      .1       0
  645.43     .06       0  792.93     .05       0 1030.12     .06       0
 1090.12     .05       0 1190.12      .1       0
Bank Sta=458.86,537
XS Rating Curve= 0 ,0
Exp/Cntr(USF)=0,0
Exp/Cntr=0.3,0.1

Type RM Length L Ch R = 1 ,16493   ,530.1,484.2,450.3
BEGIN DESCRIPTION:
Structure XS 4
END DESCRIPTION:
XS GIS Cut Line= 6
2186081.31213142640690.7655960022186492.58788368640504.420168176
2186587.46367818640467.3585624992186659.63315326640436.393073261
2186917.23237559640310.7985081672187506.70952869640042.026032051
#Sta/Elev= 30
       0 2139.86    29.5 2119.14      62 2099.95    95.4    2085   157.5 2062.64
   168.6 2056.48   187.7 2051.46     289    2005     314 1987.99   341.8 1963.71
     369 1944.87   426.5 1911.57   447.6 1885.83   459.7 1884.28   472.6 1886.29
   489.7 1875.53   498.3 1873.86   561.7 1875.68   571.6 1880.66   606.4 1881.03
   691.6 1877.59   894.5 1878.04     932 1873.62   978.9 1874.21   996.5 1882.44
  1009.5 1885.99  1088.8 1890.61  1141.5 1898.83  1387.7 1914.23  1566.4 1937.58
#Mann= 6 ,-1,0
       0      .1       0   489.7    .045       0   561.7      .1       0
  691.91     .06       0  848.82     .05       0  1058.5      .1       0
Bank Sta=489.7,561.7
XS Rating Curve= 0 ,0
Exp/Cntr(USF)=0,0
Exp/Cntr=0.3,0.1

Type RM Length L Ch R = 1 ,16009   ,89.1,85.1,86.4
BEGIN DESCRIPTION:
Structure XS 3
END DESCRIPTION:
XS GIS Cut Line= 4
2186217.34988318640969.8052915282186881.48141977 640951.65962113
2186930.47472985640586.9316461162187598.38264659640094.653082959
#Sta/Elev= 30
       0 2106.85    74.9 2075.07    94.9 2071.65   170.9 2041.28     375 1972.07
     523 1935.09   590.5 1922.76   615.2 1913.07   659.1 1912.14   707.2  1907.5
   718.8 1900.55     733 1884.73   755.7 1883.98   768.6 1874.38   782.8 1872.57
   832.4 1874.43   840.4  1880.9   844.5 1881.68   913.1 1882.27  1032.4 1877.32
  1074.2 1881.48  1123.9 1873.14  1148.8 1875.66  1228.3 1874.83  1243.2  1876.6
  1263.1 1884.35  1365.7  1900.6  1701.4 1916.55  1809.7 1928.71  1862.1 1937.93
#Mann= 7 ,-1,0
       0      .1       0   768.6    .045       0   832.4      .1       0
  914.38     .06       0 1014.38     .08       0 1052.38     .05       0
 1302.38      .1       0
Bank Sta=768.6,832.4
XS Rating Curve= 0 ,0
Exp/Cntr(USF)=0,0
Exp/Cntr=0.3,0.1

Type RM Length L Ch R = 1 ,15924   ,154.9,172.7,176.5
BEGIN DESCRIPTION:
Structure XS 2
END DESCRIPTION:
XS GIS Cut Line= 4
2186219.16445022641049.6462412832186952.24953433641027.871436804
 2187010.3156796640641.3686573122187637.00492755640154.978475411
#Sta/Elev= 30
       0 2074.68      33 2067.23      53 2056.87   137.1 2027.04   409.5 1938.58
   493.2 1922.54     512 1921.33   533.2 1912.66   597.3 1912.05   657.3 1907.57
   677.3 1891.73     701 1892.68   733.3 1902.95   760.5 1899.99   821.1  1890.3
   853.4 1882.34   869.3 1873.57   932.6 1871.53   946.1 1873.59   962.6 1878.82
   978.8 1879.85  1288.6  1873.1  1313.9 1883.79  1359.5 1886.57  1405.1 1893.13
  1496.4 1896.93  1688.6 1911.34  1761.4 1912.38  1881.3 1925.59  1917.5 1932.46
#Mann= 9 ,-1,0
       0      .1       0     630     .05       0     730     .07       0
  863.41      .1       0   869.3    .045       0   946.1      .1       0
  963.41     .07       0 1174.25     .05       0 1184.25      .1       0
Bank Sta=869.3,946.1
XS Rating Curve= 0 ,0
Exp/Cntr(USF)=0,0
Exp/Cntr=0.3,0.1

Type RM Length L Ch R = 1 ,15751   ,628.9,651.6,704.3
BEGIN DESCRIPTION:
Structure XS 1
END DESCRIPTION:
XS GIS Cut Line= 6
 2186779.1676911641309.6206575042186932.90327601641277.214882419
2187011.93953526641208.9640346772187147.80146825640879.636609346
2187215.15205534640730.0151894242187593.90678007640470.288445954
#Sta/Elev= 30
       0  1886.9    21.5 1886.44   193.9 1891.79   274.3  1896.8   334.8 1897.66
     378 1901.93   408.2 1902.59   481.7  1894.5   494.6 1884.22     512 1882.64
   525.3 1875.41   536.4 1872.42   594.4 1871.57   610.8 1872.41   629.3 1873.65
     641 1876.69   651.4 1877.27   686.8 1875.11     761 1877.02   821.9 1872.59
     851 1874.38   875.3  1872.9   899.5  1875.3   928.6 1884.19  1001.9 1892.64
    1045 1897.56  1094.6 1899.72  1132.3 1904.03  1151.7  1902.9  1241.1 1907.25
#Mann= 13 ,-1,0
       0     .06       0      50     .05       0      70     .06       0
  351.54     .05       0  385.29     .08       0  492.79     .06       0
   536.4    .045       0   610.8      .1       0  702.89     .06       0
   821.9     .05       0  1001.9     .06       0  1061.9      .1       0
  1171.9     .06       0
Bank Sta=536.4,610.8
XS Rating Curve= 0 ,0
Exp/Cntr(USF)=0,0
Exp/Cntr=0.3,0.1

Type RM Length L Ch R = 1 ,15100   ,826,848,903.6
XS GIS Cut Line= 2
2186846.32279126641331.1531988992188052.99003204641241.770440322
#Sta/Elev= 30
       0 1886.44   114.2 1887.79   186.4 1886.18   443.1 1884.49   463.1 1883.74
   471.1 1881.57   495.2 1880.71   499.2 1879.51   507.2 1874.21   515.4 1871.99
   563.4 1871.07   575.4 1871.24   583.4 1873.75   603.5 1871.23   651.6 1874.71
   703.8 1873.07   735.9 1876.29   761.6  1874.8   770.9 1872.54   776.6 1871.64
   828.9 1872.56   832.1 1874.05   840.1 1881.13   864.2 1896.36   884.3 1905.48
   940.4 1926.25  1024.7 1967.55    1157 2041.32  1181.1 2046.26    1210 2049.32
#Mann= 6 ,-1,0
       0     .06       0      10     .07       0     100     .05       0
     600      .1       0   770.9    .045       0   828.9      .1       0
Bank Sta=770.9,828.9
XS Rating Curve= 0 ,0
Exp/Cntr(USF)=0,0
Exp/Cntr=0.3,0.1

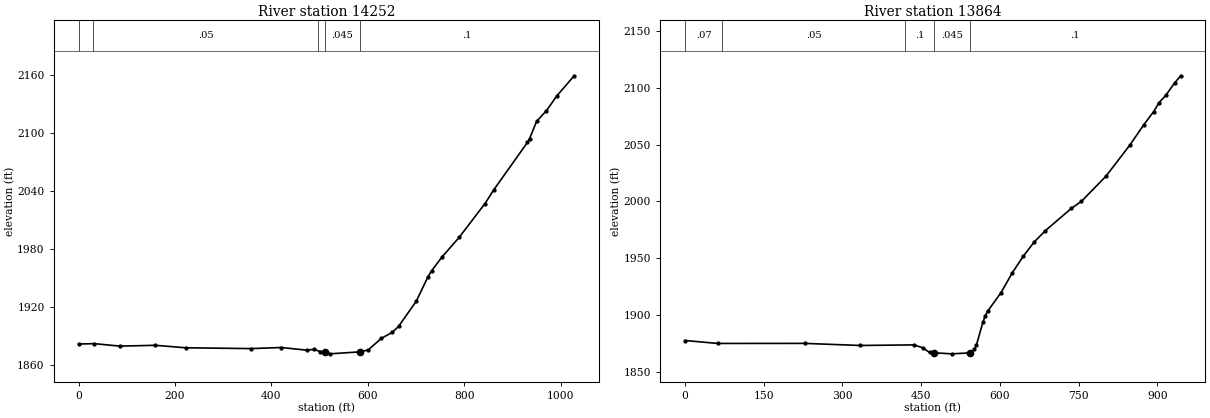
Type RM Length L Ch R = 1 ,14252   ,384.1,388,394.7
XS GIS Cut Line= 6
 2186730.8095201641405.5840482562186836.18726209641469.141992003
2187079.41577826641937.9232066722187121.25362109642014.792475507
2187168.05733326642096.1259742532187267.87307851642264.373997346
#Sta/Elev= 30
       0 1881.56    32.8 1881.88    85.2 1879.35   159.2 1880.18   222.2 1877.62
   357.5 1876.78   420.5 1877.91   473.2 1875.15   488.1 1875.97   501.6 1873.69
   511.8 1873.37   520.7 1871.35   582.8 1873.37   600.8 1875.34   627.8 1887.28
   651.2 1893.69     664 1899.86   700.4 1925.69   724.9  1951.1   732.3 1957.24
   754.3 1971.81   789.5 1991.84   843.1 2026.88   861.6 2041.27   931.3 2090.24
   935.6 2094.04   950.2 2111.99   970.6 2122.99   991.8 2138.07  1028.2 2159.14
#Mann= 5 ,-1,0
       0     .06       0      30     .05       0  496.19      .1       0
   511.8    .045       0   582.8      .1       0
Bank Sta=511.8,582.8
XS Rating Curve= 0 ,0
Exp/Cntr(USF)=0,0
Exp/Cntr=0.3,0.1

Type RM Length L Ch R = 1 ,13864   ,348.5,355.3,365
BEGIN DESCRIPTION:
Weir
END DESCRIPTION:
XS GIS Cut Line= 2
2186509.11922946641534.6000319612186827.67655423642423.737881496
#Sta/Elev= 30
       0 1877.34    62.2 1874.77   227.9 1874.82   334.2 1872.98   436.2  1873.5
   453.1 1870.93   465.9 1866.81   474.4 1866.51   508.4 1865.61   542.7 1866.45
   550.9 1869.45     555    1873   567.5  1893.3   572.1 1899.21   576.4 1903.01
   601.9 1919.33   623.8 1937.13   644.3 1951.47   665.6 1964.27   686.8 1974.17
   736.4 1993.83   755.2 1999.86   802.1 2022.07   848.3 2049.87     874 2067.27
   893.1 2079.01   903.5 2087.01   916.3 2093.39   932.8 2104.12   944.5 2110.57
#Mann= 5 ,-1,0
       0     .07       0      70     .05       0     420      .1       0
   474.4    .045       0   542.7      .1       0
Bank Sta=474.4,542.7
XS Rating Curve= 0 ,0
Exp/Cntr(USF)=0,0
Exp/Cntr=0.3,0.1