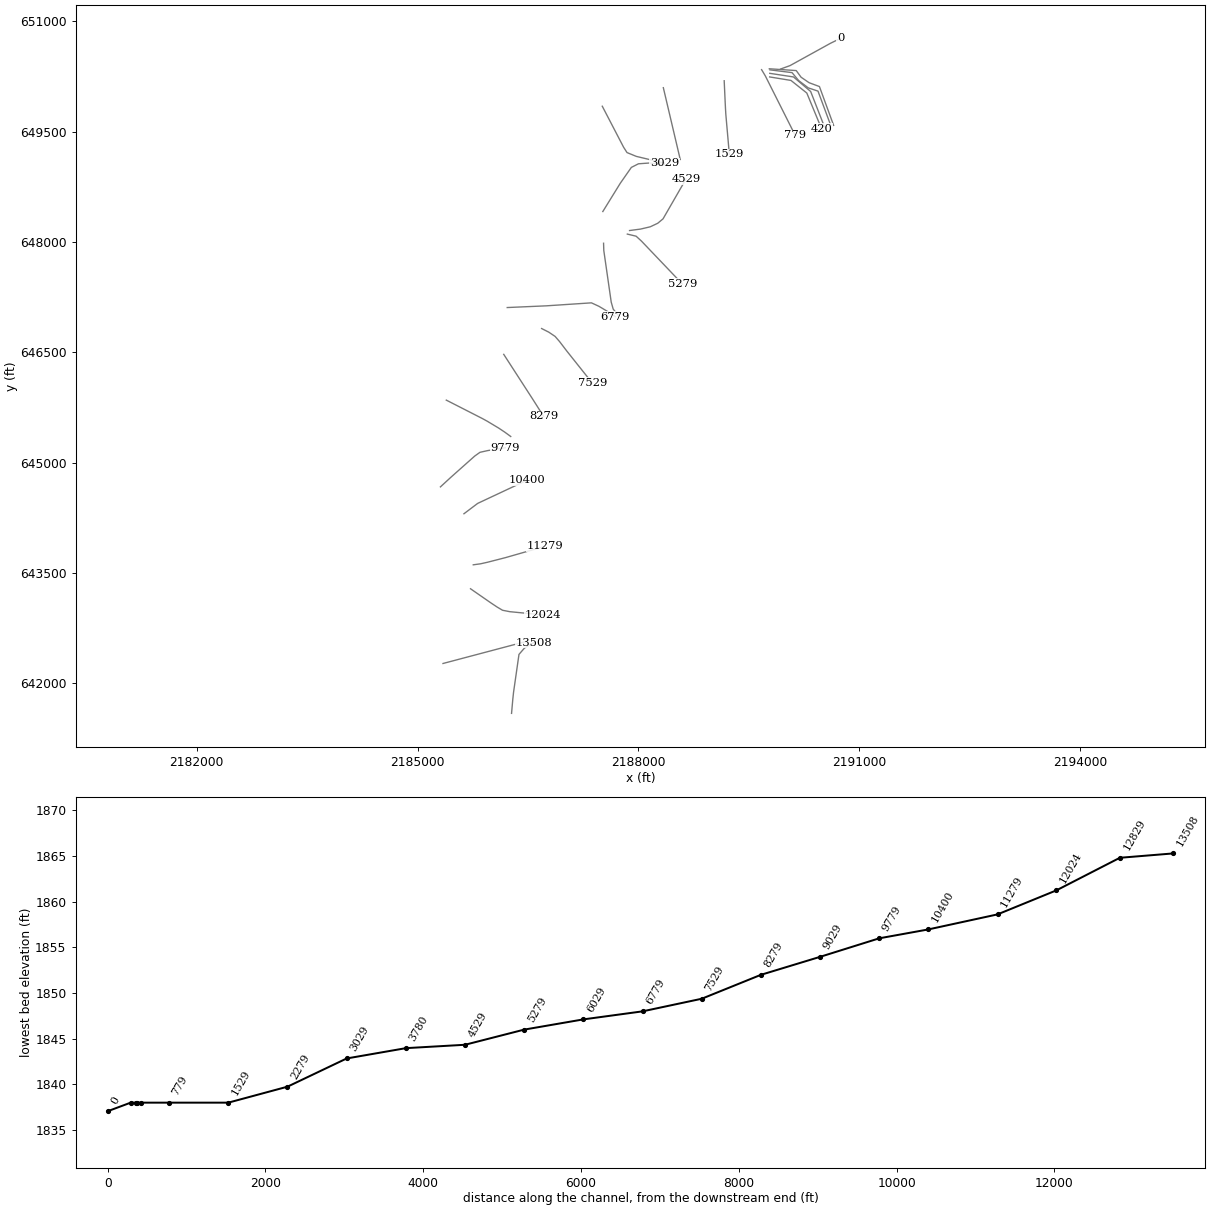
HEC-RAS study RFBUCKRV.prj: RFBUCKRV

--- RFBUCKRV.g01 (geometry) --- (continued)

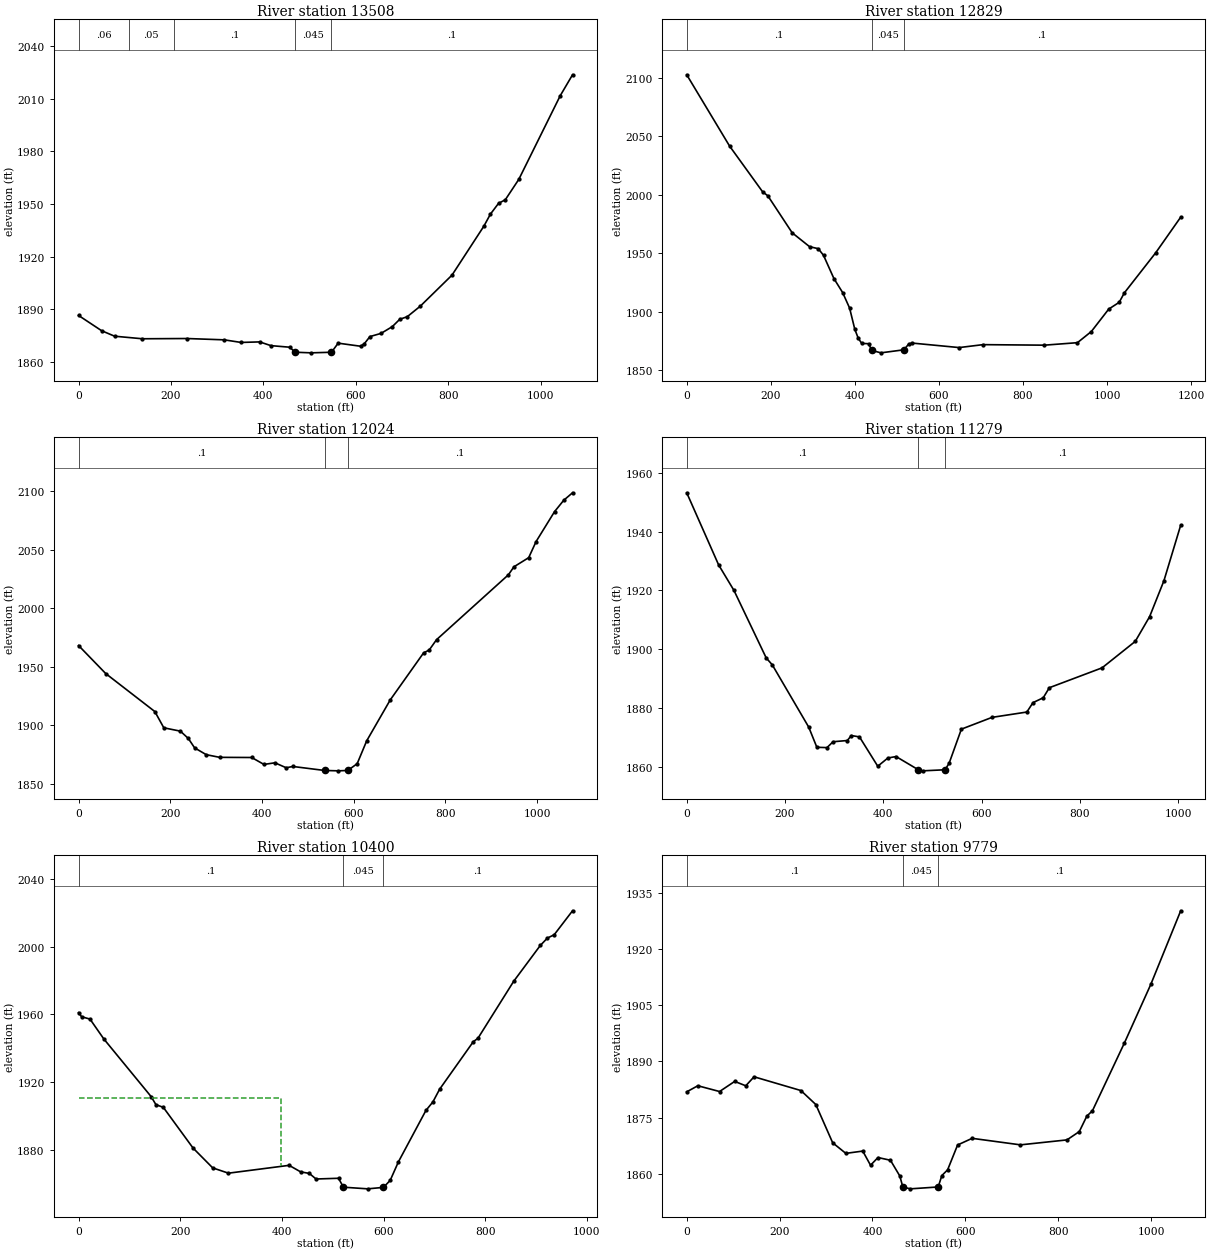
Type RM Length L Ch R = 1 ,13508   ,717.9,679.5,617.7
XS GIS Cut Line= 6
 2186276.8396275641591.4225873352186294.26708609641786.241423428
2186304.23327351641879.5237171652186377.71901892642393.042703256
2186452.27103518642479.1252082592186578.98206784642553.534180179
#Sta/Elev= 30
       0 1886.59    49.9  1877.9      78 1874.77   138.3 1873.31   234.8 1873.45
   315.3  1872.7   351.7 1871.22     392 1871.53   416.3  1869.4   456.7 1868.51
   468.8 1865.65   503.1  1865.3  547.351865.632   561.8 1870.81   610.3 1869.06
   618.4 1870.48   630.5 1874.55   654.7 1876.39     679 1880.23   695.1 1884.41
   711.3 1885.87   739.6 1891.89   808.2 1909.56   877.1 1937.41   891.3 1944.28
   908.9 1950.42   923.5 1952.45   952.7 1964.06  1042.5 2011.77    1069 2023.62
#Mann= 5 ,-1,0
       0     .06       0   108.6     .05       0   205.6      .1       0
   468.8    .045       0  547.35      .1       0
Bank Sta=468.8,547.35
XS Rating Curve= 0 ,0
Exp/Cntr(USF)=0,0
Exp/Cntr=0.3,0.1

Type RM Length L Ch R = 1 ,12829   ,822.5,804.7,775.5
XS GIS Cut Line= 2
2185345.63331831642269.6721639562186481.73522338642570.750929688
#Sta/Elev= 30
       0 2102.33   101.9 2041.46   180.6 2002.34     193 1998.94   250.9 1967.35
   292.3 1955.49     313 1953.79   325.4 1948.14   350.2 1928.26   370.9 1916.33
   387.5 1903.06   399.9 1884.89   408.2 1877.19   416.4 1872.87     433 1872.63
     440 1866.91     462 1864.82   516.6 1867.41   528.3 1872.42   536.4 1873.16
   648.2 1869.32     705 1871.82   850.9 1871.37   929.6  1873.5   962.7 1883.04
    1004 1902.17  1028.9 1907.97  1041.3  1916.1  1115.8  1950.3  1175.3 1980.73
#Mann= 3 ,-1,0
       0      .1       0     440    .045       0   516.6      .1       0
Bank Sta=440,516.6
XS Rating Curve= 0 ,0
Exp/Cntr(USF)=0,0
Exp/Cntr=0.3,0.1

Type RM Length L Ch R = 1 ,12024   ,728.2,745.7,758.1
XS GIS Cut Line= 6
2185719.43260585643285.640655592   2185996.65318643093.131198093
2186081.78818034643036.5023743362186154.91992384642993.264927998
 2186253.8577181642973.939835429 2186703.3190895642930.429751843
#Sta/Elev= 30
       0 1968.35    59.2  1944.4   166.4 1911.89   185.9 1898.02   222.1 1895.16
   239.4 1888.89   253.1 1880.86   278.5 1875.06   307.7 1872.78   377.5 1872.65
   404.2 1866.74   428.2 1868.11   452.7 1863.89   467.3 1864.98   536.3 1861.57
   566.7 1861.25   587.1 1861.59   607.5 1867.34   628.3 1886.91   679.6 1921.85
   752.4  1962.1   764.5 1964.45   780.6 1973.34   937.3 2028.79   949.3  2035.6
   981.5 2043.42   997.6 2057.17  1037.8 2082.71  1057.9 2092.47  1077.1 2098.87
#Mann= 3 ,-1,0
       0      .1       0   536.3    .045       0   587.1      .1       0
Bank Sta=536.3,587.1
XS Rating Curve= 0 ,0
Exp/Cntr(USF)=0,0
Exp/Cntr=0.3,0.1

Type RM Length L Ch R = 1 ,11279   ,870,878.8,887.5
XS GIS Cut Line= 6
2185756.92596917 643611.317825752185855.71350126 643624.88636817
2185950.49087076643646.2272047552186126.23395759643691.328164428
2186198.89982276643710.1722868382186729.07067843643862.166405424
#Sta/Elev= 30
       0  1953.2    64.9 1928.66    96.1 1919.98   161.7 1897.02     174 1894.68
   248.2 1873.48   264.7 1866.63   285.3 1866.52   297.7 1868.52   326.6 1868.93
   334.9 1870.63   351.4 1870.16   388.6 1860.19   409.2 1862.99   425.8 1863.48
   471.3 1858.97   479.7 1858.62   525.4 1858.98   533.8 1861.21   558.7  1872.8
   621.1 1876.81   691.9 1878.62   704.4 1881.82   725.2 1883.47   737.7  1886.9
   844.9 1893.65   912.4 1902.65   941.6 1911.06   970.7 1923.26  1004.9 1942.19
#Mann= 3 ,-1,0
       0      .1       0   471.3    .045       0   525.4      .1       0
Bank Sta=471.3,525.4
XS Rating Curve= 0 ,0
Exp/Cntr(USF)=0,0
Exp/Cntr=0.3,0.1

Type RM Length L Ch R = 1 ,10400   ,604.8,620.3,630
XS GIS Cut Line= 3
2185630.22021053644305.5493275352185816.80021141644446.276401739
2186484.85869894644760.129076151
#Sta/Elev= 30
       0 1961.03       6 1958.62    22.5 1957.24    49.7 1945.51   142.7 1911.48
   152.2 1906.71   166.8 1905.09   225.2 1881.08   263.9 1869.35   294.9 1866.22
   414.2 1870.85   436.9    1867     454 1866.08   467.2 1862.78   511.4 1863.21
   521.1 1857.94   568.9 1856.97   599.8 1857.83   613.1 1861.98   629.3 1872.94
   683.4 1903.29   697.1 1908.31   710.3  1915.8   776.6 1943.89   785.7 1945.89
   856.1 1979.59   908.4 2000.73   922.4  2005.1   935.7 2007.05   971.8 2021.21
#Mann= 3 ,-1,0
       0      .1       0   521.1    .045       0   599.8      .1       0
#XS Ineff= 2 , 0
          398.99 1910.34
Permanent Ineff=
       F       F
Bank Sta=521.1,599.8
XS Rating Curve= 0 ,0
Exp/Cntr(USF)=0,0
Exp/Cntr=0.3,0.1

Type RM Length L Ch R = 1 ,9779    ,795.3,750,694.4
XS GIS Cut Line= 6
2185310.73427625644670.6926755012185454.44199409644803.002122179
2185776.54764909645089.7502363322185848.22368684645140.830186665
2185953.72675668645164.3114389182186191.69708125645202.746073335
#Sta/Elev= 30
       0 1881.87    23.9 1883.49    70.7 1881.95   103.3 1884.65   127.1 1883.48
     145 1885.88   245.9 1882.21     278 1878.48   314.3 1868.28   342.6 1865.46
   379.1 1866.07   395.8 1862.29   411.9 1864.35   438.7 1863.62   458.8 1859.44
   465.4 1856.49   481.5    1856   541.5  1856.5   549.4 1859.54   561.8 1861.07
   583.3 1867.69   614.6 1869.47   718.7 1867.73   818.8 1869.05   845.4 1871.27
   861.6 1875.39   873.7 1876.82   942.5 1894.89   999.3  1910.5  1063.8 1930.15
#Mann= 3 ,-1,0
       0      .1       0   465.4    .045       0   541.5      .1       0
Bank Sta=465.4,541.5
XS Rating Curve= 0 ,0
Exp/Cntr(USF)=0,0
Exp/Cntr=0.3,0.1

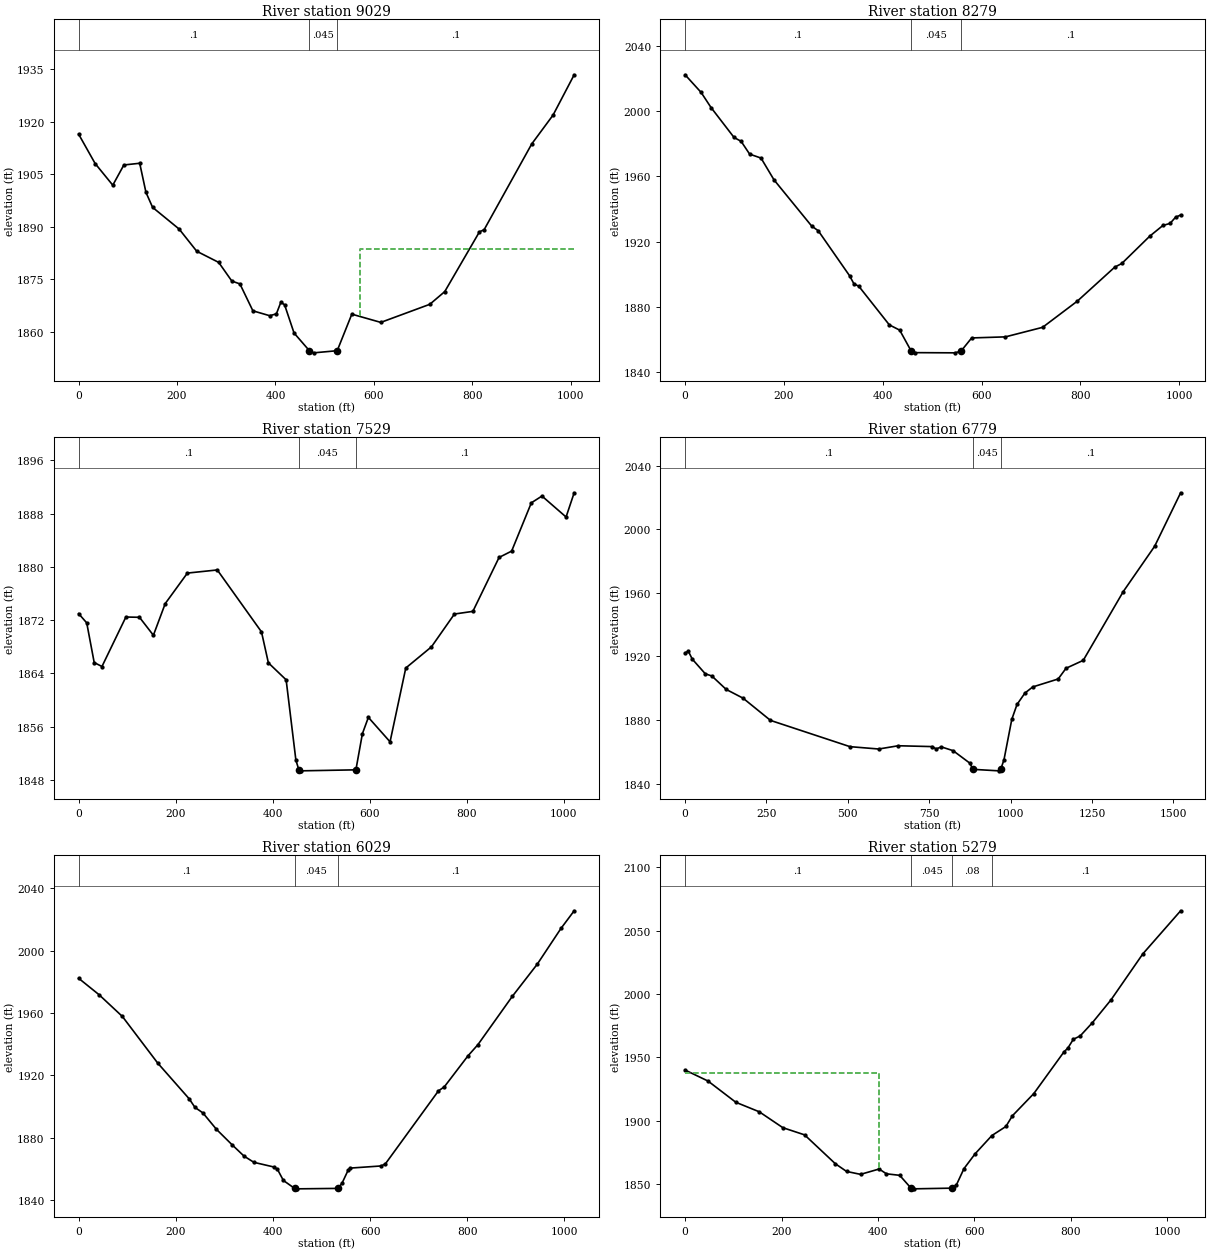
Type RM Length L Ch R = 1 ,9029    ,769.3,750,735.1
XS GIS Cut Line= 6
2185390.36567867 645850.277258592185881.54087742 645599.34272109
2185947.22447309645563.0583448412186103.02074942645469.617586836
2186184.52583575 645415.148207592186265.84424268645355.890780166
#Sta/Elev= 30
       0 1916.39    33.5 1908.02    69.4 1901.83    91.9  1907.6   124.1 1908.09
   136.8 1899.78   150.3  1895.5   204.2 1889.31     240 1882.97   284.6 1879.79
   311.3 1874.46   327.7 1873.65   354.1 1865.96   388.3 1864.57   401.8  1865.1
   410.8 1868.37   418.4 1867.72   437.7 1859.63   468.9 1854.58   477.8 1853.97
   525.4 1854.58   555.1 1865.01     614 1862.66   713.5 1867.82   743.9 1871.45
   814.5 1888.53   823.9 1889.11   920.7 1913.61     964 1921.84  1006.9 1933.35
#Mann= 3 ,-1,0
       0      .1       0   468.9    .045       0   525.4      .1       0
#XS Ineff= 2 , 0
                           571.1         1883.62
Permanent Ineff=
       F       F
Bank Sta=468.9,525.4
XS Rating Curve= 0 ,0
Exp/Cntr(USF)=0,0
Exp/Cntr=0.3,0.1

Type RM Length L Ch R = 1 ,8279    ,744.5,750.1,755.6
XS GIS Cut Line= 6
2186170.81917025646472.3852663342186224.24754108646389.708922505
 2186558.3846681645872.653526172 2186608.7172446 645793.55755575
2186660.47042193645711.6590975082186712.93324351 645628.35939534
#Sta/Elev= 30
       0 2022.14    32.4 2011.36    52.5  2002.1    99.1 1983.79   113.4 1981.42
   130.6 1973.61   153.7 1971.17     180 1957.83   256.2 1929.58   269.5 1926.72
   333.1  1899.1   341.8 1894.19   351.5  1892.8   413.4 1869.11   434.4 1865.89
   457.5 1853.18   465.8 1852.12   546.7    1852   558.71853.113   580.1 1861.12
   648.4 1861.77   723.7 1867.61     794 1883.64   869.8 1904.46     884 1906.67
   940.7 1923.42   967.2 1929.93   981.7  1931.2   992.7 1934.93  1003.1 1936.35
#Mann= 3 ,-1,0
       0      .1       0   457.5    .045       0   558.7      .1       0
Bank Sta=457.5,558.7
XS Rating Curve= 0 ,0
Exp/Cntr(USF)=0,0
Exp/Cntr=0.3,0.1

Type RM Length L Ch R = 1 ,7529    ,679.4,749.9,800.5
XS GIS Cut Line= 6
2186685.33126459646823.7126476762186783.16899543646773.950280011
2186868.93325959646716.2072852552186930.42034134    646644.93479
2187029.00052476646515.7070300882187372.46046776646084.132433921
#Sta/Elev= 30
       0 1872.99    16.7  1871.6    32.1 1865.64    48.1 1865.05    97.4 1872.48
   125.4 1872.44   154.1 1869.74   178.5  1874.5   224.2 1879.08   285.8 1879.55
   376.9 1870.25   391.1  1865.6   427.7 1863.05   447.8 1850.99   453.9 1849.54
   457.9 1849.38   571.5 1849.53   584.9 1854.96   597.2 1857.41   641.9 1853.74
   674.3 1864.82   727.2    1868   774.6 1872.93   812.6 1873.33   866.6 1881.43
   892.5 1882.38   933.1 1889.63     955 1890.65  1004.7  1887.5  1021.4 1891.14
#Mann= 3 ,-1,0
       0      .1       0   453.9    .045       0   571.5      .1       0
Bank Sta=453.9,571.5
XS Rating Curve= 0 ,0
Exp/Cntr(USF)=0,0
Exp/Cntr=0.3,0.1

Type RM Length L Ch R = 1 ,6779    ,828.6,750,685.9
XS GIS Cut Line= 6
2186218.13564741647108.9269475552186748.00272718647132.168723673
2187362.28594743647172.7959389982187464.33069085647125.652004421
2187574.40888275647059.8253644262187687.60124168646985.327153832
#Sta/Elev= 30
       0 1922.28      10 1923.26    22.1 1918.31    62.1 1909.07    82.1 1907.72
   126.2 1899.26   178.2 1893.72   262.3 1879.75   506.5 1863.22   594.7 1861.74
   654.8 1863.79   759.1 1863.26   771.1 1861.79   787.1 1863.07   823.2  1860.7
   875.3 1852.74883.53921848.953   963.3    1848  969.59 1848.99   979.5 1854.93
  1003.6 1880.45  1019.6 1889.78  1043.7 1896.91  1067.7  1900.8    1146 1905.82
  1170.1 1912.55    1223 1917.54  1346.1 1960.88  1442.4 1989.37  1522.2 2023.03
#Mann= 3 ,-1,0
       0      .1       0883.5392    .045       0  969.59      .1       0
Bank Sta=883.5392,969.59
XS Rating Curve= 0 ,0
Exp/Cntr(USF)=0,0
Exp/Cntr=0.3,0.1

Type RM Length L Ch R = 1 ,6029    ,710.5,750,771.3
XS GIS Cut Line= 6
2187527.03266518647983.223123923  2187530.130428647884.219384924
2187569.69563758647608.9230194992187631.04459625 647182.05904384
2187657.76567142647088.0290481752187729.27963601646999.428831667
#Sta/Elev= 30
       0 1982.19    42.1 1971.63    90.1 1957.68   162.7 1927.82   227.4 1904.93
   239.5 1899.35   255.7 1895.85   283.7 1885.29   315.5  1875.5   340.5  1868.1
   360.8 1864.12   401.2 1861.18   409.2 1859.66   421.5 1852.48  444.541847.415
   449.7 1847.12   534.4  1847.4   542.6 1851.02   554.7 1859.07   558.8 1860.42
   622.9 1861.81   631.5 1863.19   740.6 1909.95   752.7 1912.55   801.2 1932.35
   821.8 1939.58   892.5 1970.52   944.1 1991.26   992.8 2014.15    1020 2025.49
#Mann= 3 ,-1,0
       0      .1       0  444.54    .045       0   534.4      .1       0
Bank Sta=444.54,534.4
XS Rating Curve= 0 ,0
Exp/Cntr(USF)=0,0
Exp/Cntr=0.3,0.1

Type RM Length L Ch R = 1 ,5279    ,670,750,829.5
XS GIS Cut Line= 6
2187849.91522151648107.6277307572187969.22994351 648078.97818175
2188040.80132267648013.3667644262188105.49574709 647945.51617834
2188165.87751609647882.1895333382188598.25296368647428.722920582
#Sta/Elev= 30
       0 1939.88    47.6 1931.17   105.2  1914.4   153.8 1906.89   202.7 1894.33
   247.8 1888.65   311.6 1865.82   334.8 1859.76   363.8 1857.44   402.4 1861.67
   417.5 1857.87     445 1856.68   468.5 1846.55   474.1    1846  554.221846.549
   562.7 1849.17   578.3 1861.97   601.4 1873.69   636.2 1888.12   665.2 1895.27
   678.8 1903.77   723.1 1921.28   785.3 1954.04   793.8 1957.29   805.1 1964.19
   819.3 1966.83   844.6 1977.29   883.3 1995.39   949.2 2031.68  1027.6 2065.74
#Mann= 4 ,-1,0
       0      .1       0   468.5    .045       0  554.22     .08       0
  636.05      .1       0
#XS Ineff= 2 , 0
          402.01 1937.59
Permanent Ineff=
       F       F
Bank Sta=468.5,554.22
XS Rating Curve= 0 ,0
Exp/Cntr(USF)=0,0
Exp/Cntr=0.3,0.1

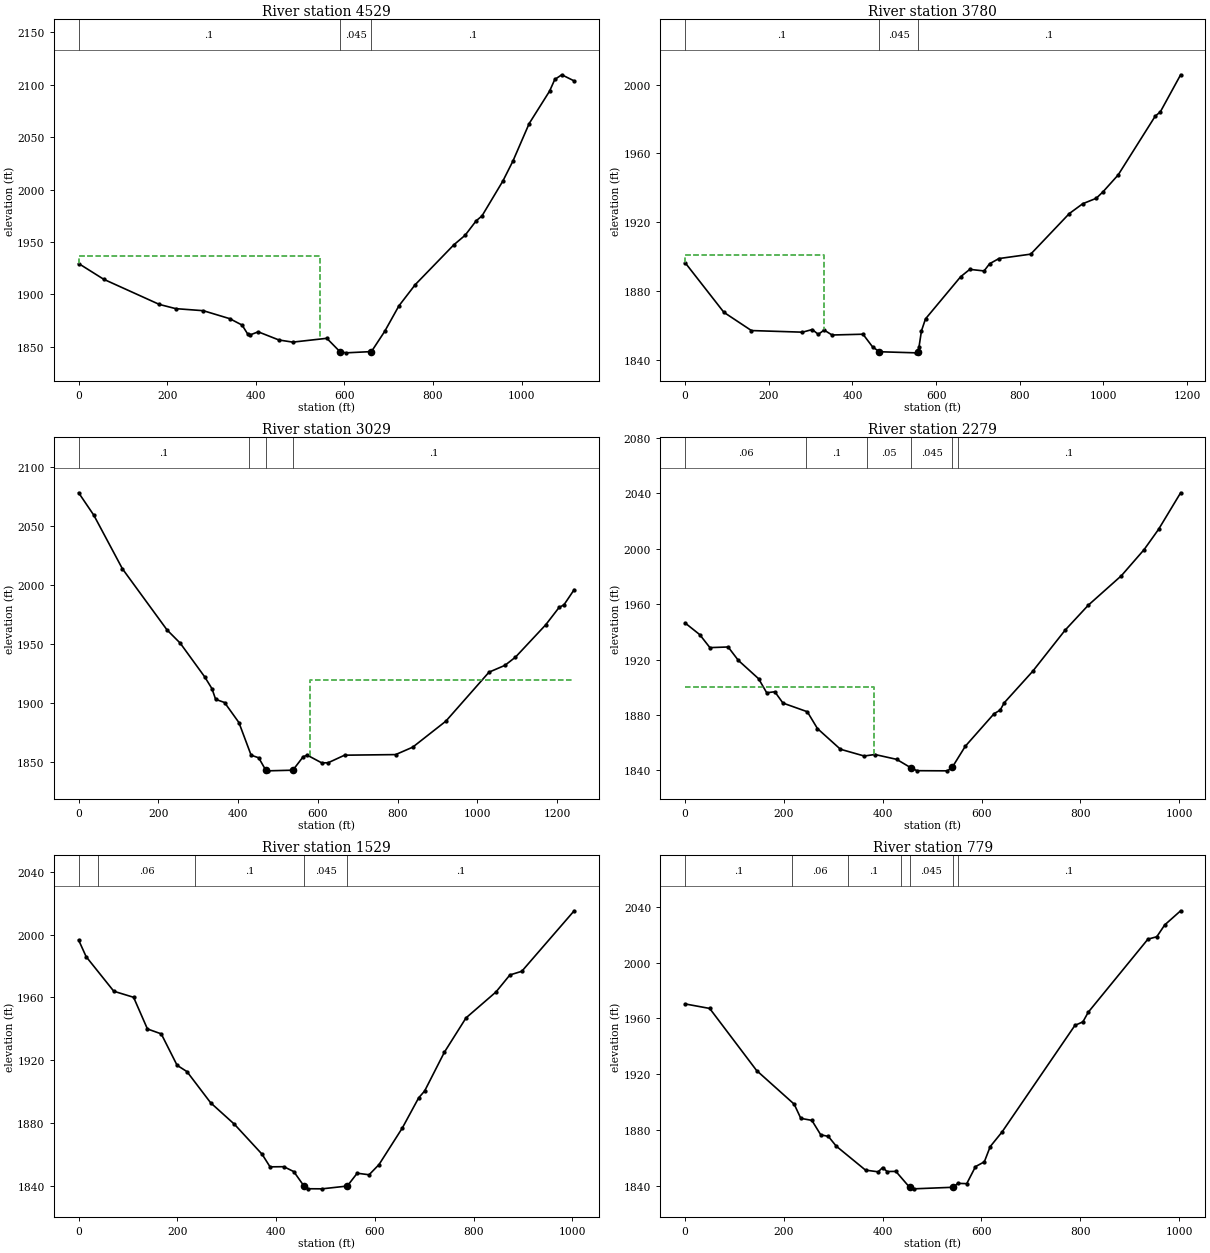
Type RM Length L Ch R = 1 ,4529    ,750.5,748.9,745.9
XS GIS Cut Line= 6
2187880.06903259648155.9973846672188029.53756568648175.717161506
2188161.41623892648206.8447239252188262.77135117648254.783276334
2188334.76070851648314.5892590882188647.46283901648857.564223006
#Sta/Elev= 30
       0 1929.53    56.6 1914.52   182.2 1890.52   219.2  1886.5   281.5 1884.53
   341.2 1876.92     369 1870.83   382.2 1861.92   386.2 1861.28   405.4 1864.39
   452.2 1856.59   483.4 1854.56   560.3 1858.19   589.8 1845.49   603.5 1844.34
     661 1845.53   690.9 1864.79     723 1889.13   759.8 1909.34   847.1  1947.4
   872.4 1956.43   897.7 1970.39   910.5 1974.89   957.7  2008.2   980.4 2027.23
  1017.1 2063.06  1063.2    2094  1074.9  2105.1  1090.7 2109.57  1118.7 2103.72
#Mann= 3 ,-1,0
       0      .1       0   589.8    .045       0     661      .1       0
#XS Ineff= 2 , 0
          545.22 1936.38
Permanent Ineff=
       F       F
Bank Sta=589.8,661
XS Rating Curve= 0 ,0
Exp/Cntr(USF)=0,0
Exp/Cntr=0.3,0.1

Type RM Length L Ch R = 1 ,3780    ,830.5,751.1,645.1
XS GIS Cut Line= 6
2187516.92671426648414.2750833332187754.04369409648798.572215006
2187904.43381326649014.2259831732188000.97003751649063.374506921
2188151.65379126649074.0398399232188360.38598534649047.275785834
#Sta/Elev= 30
       0 1896.47    92.7 1867.56   158.5 1856.94   280.6    1856   303.9 1857.53
   318.3 1854.75   332.4 1857.21   351.2 1854.35   425.2 1854.81     448 1847.47
   464.2 1844.61   551.2 1843.97     5561844.656   559.1 1847.38   564.9 1856.73
   574.6 1863.74   658.6 1888.27   680.4 1892.56   714.6 1891.64   727.8 1895.84
   750.2 1898.85   826.1 1901.42   918.3 1925.04   950.4 1930.76   982.6 1933.92
   998.7 1937.66    1035  1947.5  1123.7 1981.76  1135.8 1984.21  1184.4 2005.82
#Mann= 3 ,-1,0
       0      .1       0   464.2    .045       0     556      .1       0
#XS Ineff= 2 , 0
             333 1901.14
Permanent Ineff=
       F       F
Bank Sta=464.2,556
XS Rating Curve= 0 ,0
Exp/Cntr(USF)=0,0
Exp/Cntr=0.3,0.1

Type RM Length L Ch R = 1 ,3029    ,759.2,750,739
XS GIS Cut Line= 6
2187509.54943243649845.9316688332187798.41860534649289.932452753
 2187845.6242196649215.8532045932187971.56524068 649164.18828167
2188136.95139284649124.4465632592188353.03495017649072.479147509
#Sta/Elev= 30
       0 2078.24    38.1 2059.25   109.8  2013.9   221.7 1962.14   254.7 1950.98
   316.4 1922.29   334.4 1912.42   343.6 1903.39     366 1900.68     402 1883.73
   432.6  1856.1   451.6 1853.89  469.281843.497   474.2 1842.84   537.3 1843.39
   563.2 1854.77   573.3 1856.14   609.4 1849.64   625.5 1849.64     667 1856.09
   795.1 1856.59     838 1862.89   921.1  1884.9  1029.3 1926.37  1069.2 1932.14
  1095.7  1939.1  1171.5 1966.46  1205.1 1981.17  1217.3  1983.4  1242.9 1996.21
#Mann= 4 ,-1,0
       0      .1       0  426.56     .06       0  469.28    .045       0
   537.3      .1       0
#XS Ineff= 2 , 0
                          579.73         1919.48
Permanent Ineff=
       F       F
Bank Sta=469.28,537.3
XS Rating Curve= 0 ,0
Exp/Cntr(USF)=0,0
Exp/Cntr=0.3,0.1

Type RM Length L Ch R = 1 ,2279    ,756.8,750.1,743.2
XS GIS Cut Line= 6
2188338.94016209650097.9971095922188361.48670493650002.176435083
2188425.18834917649731.4446930892188442.36646442649658.438605502
2188546.14939334649217.3587789982188568.69560809649121.538104504
#Sta/Elev= 30
       0 1946.41    29.6 1938.01    50.2 1928.63    87.1 1929.09   107.7 1919.46
   148.8 1906.19   165.2 1896.05   181.6  1896.8   198.1 1888.63   247.4 1882.38
   267.9 1870.25   314.4 1855.33   362.5 1850.45   384.3 1851.53   428.2 1848.04
     457 1841.96   469.3 1839.86   530.9 1839.75   540.6 1842.21   567.2 1857.49
   625.4 1880.95   637.8 1883.57     646 1888.84   703.4 1911.46   769.3 1941.24
   816.2 1959.25   883.2 1980.52   929.1 1999.31   958.3 2013.89  1003.1 2040.32
#Mann= 6 ,-1,0
       0     .06       0  245.31      .1       0  369.06     .05       0
     457    .045       0   540.6     .05       0  551.56      .1       0
#XS Ineff= 2 , 0
          382.17    1900
Permanent Ineff=
       F       F
Bank Sta=457,540.6
XS Rating Curve= 0 ,0
Exp/Cntr(USF)=0,0
Exp/Cntr=0.3,0.1

Type RM Length L Ch R = 1 ,1529    ,730,749.9,767.3
XS GIS Cut Line= 6
2189165.81318025650192.3499392572189178.97457126   649903.325911
2189183.32364392649815.8697210852189187.61858284 649740.95714125
2189196.19763392649641.3257788422189235.88521859649191.510405511
#Sta/Elev= 30
       0 1996.59    15.2 1986.01    71.2 1963.97   111.3 1960.11   139.3 1939.93
   167.3 1936.79   199.4 1916.76   219.4 1912.73   267.4 1892.84   315.5 1879.17
   371.6 1860.03   387.6 1852.03   415.6 1852.11   435.7 1848.99   455.9 1839.99
   463.7 1838.06   492.9    1838     544 1839.78   564.1 1847.96   588.2 1846.97
   608.3 1853.48   655.4 1876.74   688.6 1896.02   700.6 1900.34   740.8 1925.17
   784.5 1946.98   845.2 1963.52   873.3 1974.34   897.4 1976.68  1003.5 2015.26
#Mann= 5 ,-1,0
       0      .1       0      40     .06       0  235.49      .1       0
   455.9    .045       0     544      .1       0
Bank Sta=455.9,544
XS Rating Curve= 0 ,0
Exp/Cntr(USF)=0,0
Exp/Cntr=0.3,0.1

Type RM Length L Ch R = 1 ,779     ,337.1,359.7,383.5
BEGIN DESCRIPTION:
Structure 2 XS 4
END DESCRIPTION:
XS GIS Cut Line= 6
  2189673.815117650343.095372677 2189724.4728241650258.383599833
2189810.05008076650088.0473263412189883.00072226649942.842564255
2190042.93150476649624.5088833422190130.61308792649449.983969927
#Sta/Elev= 30
       0  1970.4    49.8 1967.17   144.8 1922.72   220.9 1898.62   234.3 1888.47
   256.7 1887.02   274.6  1876.7   290.1 1875.54     306 1868.59   365.3 1851.41
     391 1850.18     400 1853.26   408.9 1850.41   426.8 1850.49   454.4 1839.17
   462.6    1838   542.9 1839.13   552.2 1841.93   570.3 1841.72     588 1853.91
   605.9 1857.34   617.8 1868.24   641.7 1878.68   789.4 1955.06   805.5 1957.56
   816.3 1964.46   937.1 2016.76   955.1 2018.51   971.2 2026.99  1003.4  2037.1
#Mann= 7 ,-1,0
       0      .1       0  215.58     .06       0  329.33      .1       0
  436.83     .06       0   454.4    .045       0   542.9     .05       0
  551.83      .1       0
Bank Sta=454.4,542.9
XS Rating Curve= 0 ,0
Exp/Cntr(USF)=0,0
Exp/Cntr=0.3,0.1

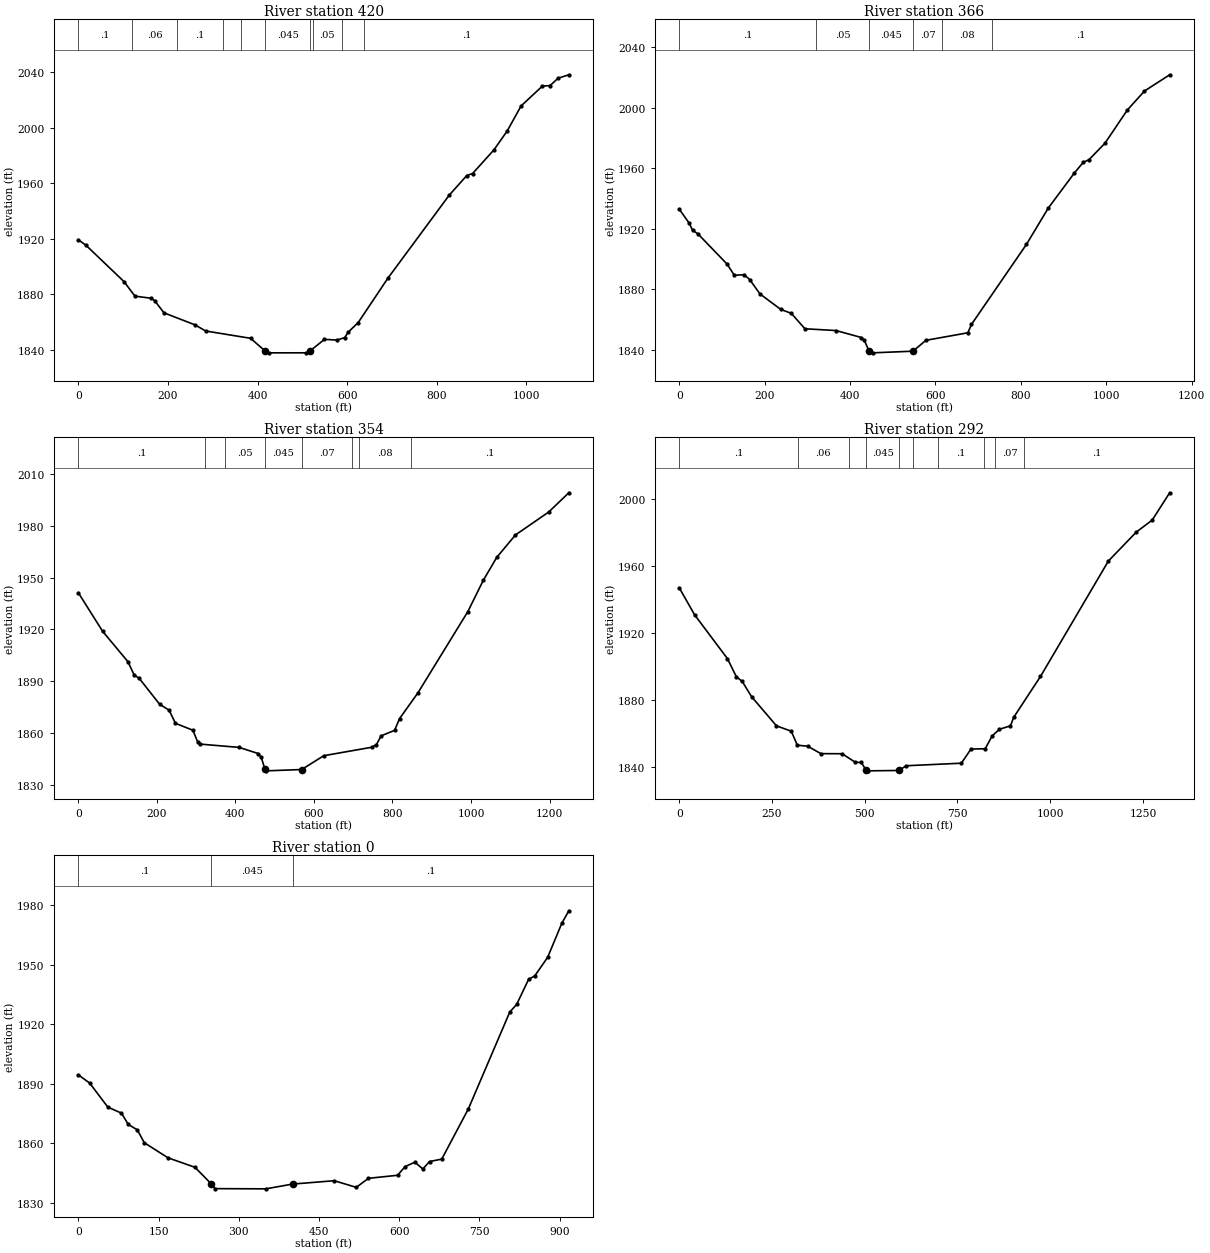
Type RM Length L Ch R = 1 ,420     ,55.7,53.7,51.8
BEGIN DESCRIPTION:
Structure 2 XS 3
END DESCRIPTION:
XS GIS Cut Line= 4
2189783.56170163 650244.157894872190072.62223108650196.797695129
2190288.19279542650025.3211098622190489.06536673649538.654229769
#Sta/Elev= 30
       0 1919.36    17.1 1915.41     102 1889.23   126.3  1878.8   162.8  1877.3
   170.3 1875.53   191.2 1866.79     260 1858.18   284.4 1853.71   384.3 1848.47
   417.4 1839.19   425.2    1838   508.7 1838.01  516.761839.284   549.3 1847.68
   577.2 1847.23   594.5 1848.93   602.2 1852.81   624.8 1859.84     691 1891.76
   828.2 1951.63   867.1 1965.64   880.1  1967.1   927.7  1984.1   957.5 1997.81
   988.3 2015.74  1035.9 2030.02  1053.2 2030.42  1070.8 2035.66  1094.9 2038.17
#Mann= 10 ,-1,0
       0      .1       0     120     .06       0     220      .1       0
  322.91     .05       0  362.91     .08       0   417.4    .045       0
  516.76     .07       0  522.91     .05       0  588.37     .08       0
  638.37      .1       0
Bank Sta=417.4,516.76
XS Rating Curve= 0 ,0
Exp/Cntr(USF)=0,0
Exp/Cntr=0.3,0.1

Type RM Length L Ch R = 1 ,366     ,9.3,12.3,17.9
BEGIN DESCRIPTION:
Structure 2 XS 2
END DESCRIPTION:
XS GIS Cut Line= 4
2189785.19481197650293.1512049462190106.91754814 650244.15789487
2190340.45232617650046.5515442282190528.26001479649564.783995144
#Sta/Elev= 30
       0 1933.02    23.7 1923.59    31.3    1919    43.5 1916.76   112.3 1896.61
     129 1889.28   151.6 1889.69   164.9  1886.5   189.1 1876.93   237.7 1866.73
   262.4 1864.12   294.3 1853.92   367.2 1852.74   426.6 1848.13   433.5 1846.22
   444.8  1838.9   452.8    1838   547.2 1839.09   577.7 1846.29   675.8 1851.26
   684.3 1856.82   813.1 1909.78   863.9 1933.66   924.8 1956.81   946.2 1964.07
   959.1 1965.66   996.7 1976.59  1049.2 1998.59  1089.4 2011.17  1148.4 2021.91
#Mann= 6 ,-1,0
       0      .1       0     320     .05       0   444.8    .045       0
   547.2     .07       0  615.43     .08       0  731.35      .1       0
Bank Sta=444.8,547.2
XS Rating Curve= 0 ,0
Exp/Cntr(USF)=0,0
Exp/Cntr=0.3,0.1

Type RM Length L Ch R = 1 ,354     ,58.2,62.2,64
BEGIN DESCRIPTION:
Structure 1 XS 3
END DESCRIPTION:
XS GIS Cut Line= 6
 2189786.8279223650340.5114046872190087.32022411650302.949866962
2190178.77440292650193.5314744582190307.79011945650095.544854305
2190440.07205666650051.450875236 2190614.8148626649581.115098502
#Sta/Elev= 30
       0 1941.28    61.8 1918.94   126.3  1901.3   142.4 1893.44   154.4 1891.82
   206.9 1876.64   231.1 1873.19   247.3 1865.57   291.6 1861.56   304.2  1854.6
   310.4  1853.5   409.4  1851.6   458.1 1848.04   465.9 1845.81   475.2 1838.84
   479.1    1838  568.791838.767     625 1846.78   747.4 1851.69   759.2 1853.26
   771.2 1858.32   805.3 1861.47   818.1 1868.31   865.1 1883.33     992  1930.4
  1031.5  1948.6  1065.6 1961.84  1113.3 1974.86  1197.9 1988.15  1249.2 1999.32
#Mann= 8 ,-1,0
       0      .1       0  322.83     .06       0  372.83     .05       0
   475.2    .045       0  568.79     .07       0  697.44      .1       0
  716.02     .08       0  847.43      .1       0
Bank Sta=475.2,568.79
XS Rating Curve= 0 ,0
Exp/Cntr(USF)=0,0
Exp/Cntr=0.3,0.1

Type RM Length L Ch R = 1 ,292     ,291.6,291.6,291.6
BEGIN DESCRIPTION:
Structure 1 XS 2
END DESCRIPTION:
XS GIS Cut Line= 6
2189778.66237063 650355.209397712190144.47908586650330.712742671
 2190209.8034993650240.891674198 2190319.2218918650165.768598748
2190459.66938069650113.5090679992190652.37640032 649586.01442951
#Sta/Elev= 30
       0 1946.99    41.6 1930.85   129.8 1904.86   153.9 1894.07   169.9  1891.2
     195 1882.17   262.1  1864.8   302.2 1861.58   318.2 1853.28   346.3 1852.66
   381.8 1848.24   439.1 1848.18   474.9 1843.06   490.7 1843.03     5041838.303
   509.7    1838   592.2 1838.21   611.8 1841.03   760.6 1842.55   786.5 1850.98
   824.8 1851.13   843.7 1858.85   863.2 1862.74     893 1864.82   901.6 1869.85
   973.9  1894.2    1157 1962.95  1232.2 1980.17    1275  1987.3  1322.2 2003.57
#Mann= 10 ,-1,0
       0      .1       0     320     .06       0  456.64     .05       0
     504    .045       0   592.2      .1       0  630.42     .07       0
  696.92      .1       0  820.61     .08       0  850.61     .07       0
  930.61      .1       0
Bank Sta=504,592.2
XS Rating Curve= 0 ,0
Exp/Cntr(USF)=0,0
Exp/Cntr=0.3,0.1

Type RM Length L Ch R = 1 ,0       ,470,470,470
XS GIS Cut Line= 4
2189932.37007168650351.9739080442190060.25883885650398.310417888
 2190610.7365758650702.2779224672190747.89264494650769.002496643
#Sta/Elev= 30
       0 1894.47    21.1 1890.33    55.1 1878.22    80.6 1875.18    93.4 1869.48
   110.4 1866.74   123.2  1860.3   167.5 1852.71   218.2 1847.89  248.911839.467
   255.8 1837.16   350.7 1837.06   400.6 1839.46   478.6 1841.15   519.8 1837.81
   542.6 1842.36   597.1 1843.89   611.1 1848.27   629.4 1850.47   644.4 1847.06
   656.8 1850.81   679.7 1852.03   729.5 1877.34     807 1926.14   819.8 1929.93
   842.1 1942.54   853.8 1944.35   877.7 1953.62   904.3 1970.81   917.4 1977.11
#Mann= 3 ,-1,0
       0      .1       0  248.91    .045       0   400.6      .1       0
Bank Sta=248.91,400.6
XS Rating Curve= 0 ,0
Exp/Cntr=0.3,0.1
LCMann Table=0

Chan Stop Cuts=-1
Use User Specified Reach Order=0
Composite Channel Slope=5